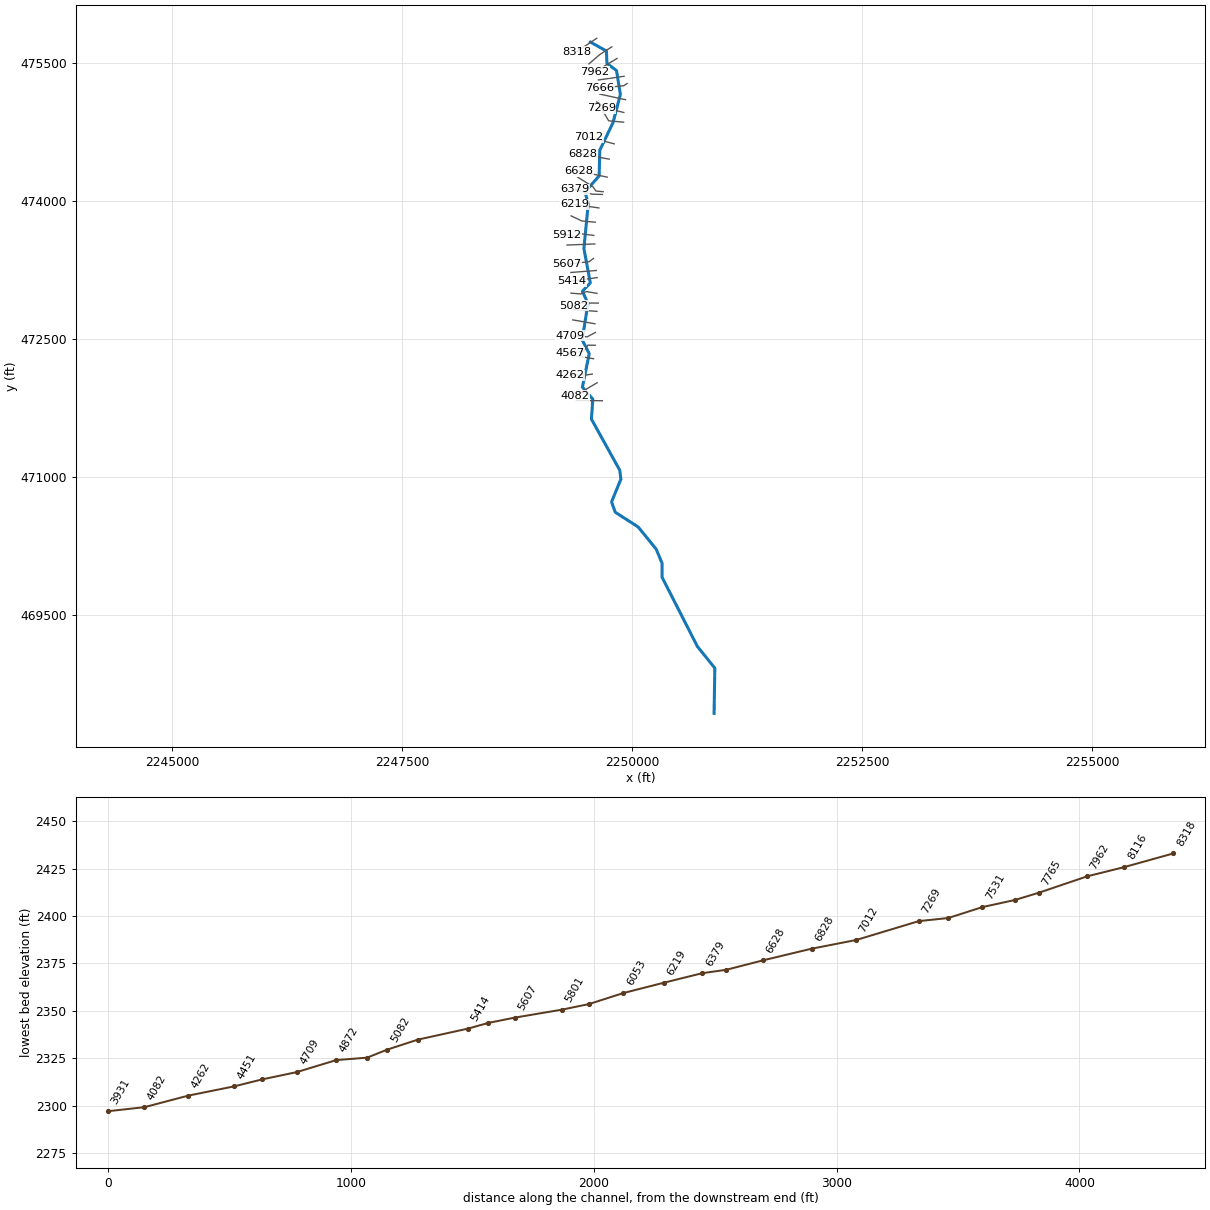
--- LAURELRN3.prj (project) ---

Proj Title=LAURELRN3
Current Plan=p01
Default Exp/Contr=0,0
English Units
Geom File=g01
Flow File=f01
Plan File=p01
Background Map Layer=Inundation Boundary (01pct Value_0)
BEGIN DESCRIPTION:
----------MODEL BY WOOD PLC 2021----------
Stream Name: Laurel Run III
Flood Zone: Enhanced Approximate
Pocahontas County, WV
HEC-RAS Version: RAS 6.1
Vertical Datum: NAVD88
Projection: NAD 1983 StatePlane West Virginia S FIPS 4702 (US Feet)
Terrain: 1-meter LIDAR (FEMA Region III 3DEP collected 2016-2018)
Land Use: 2019 NLCD
Hydrologic Method:
WV SIR2010-5033 regression equations
END DESCRIPTION:
DSS File=dss
DSS Export Rating Curves= 0
DSS Export Rating Curve Sorted= 0
DSS Export Volume Flow Curves= 0
DXF OffsetX= 0
DXF OffsetY= 0
DXF ScaleX= 0
DXF ScaleY= 0

--- LAURELRN3.p01 (plan) ---

Plan Title=Floodplain
Program Version=6.10
Short Identifier=Floodplain
Geom File=g01
Flow File=f01
Subcritical Flow
K Sum by GR= 0
Std Step Tol= 0.01
Critical Tol= 0.01
Num of Std Step Trials= 20
Max Error Tol= 0.3
Flow Tol Ratio= 0.001
Split Flow NTrial= 30
Split Flow Tol= 0.02
Split Flow Ratio= 0.02
Log Output Level= 0
Friction Slope Method= 1
Unsteady Friction Slope Method= 2
Unsteady Bridges Friction Slope Method= 1
Parabolic Critical Depth
Global Vel Dist= 0 , 0 , 0
Global Log Level= 0
CheckData=True
Encroach Param=-1 ,0,0, 0
Computation Interval=0.1SEC
Output Interval=1SEC
Instantaneous Interval=Max Profile
Mapping Interval=1HOUR
Computation Time Step Use Courant=        0
Computation Time Step Use Time Series=    0
Computation Time Step Count To Double=0
Computation Time Step Max Doubling=0
Computation Time Step Max Halving=0
Computation Time Step Residence Courant=0
Run HTab= 0
Run UNet= 0
Run Sediment= 0
Run PostProcess= 0
Run WQNet= 0
Run RASMapper=-1
UNET Theta= 0
UNET Theta Warmup= 0
UNET ZTol= 0
UNET ZSATol= 0
UNET MxIter= 0
UNET Max Iter WO Improvement= 0
UNET MaxInSteps= 0
UNET DtIC= 0
UNET DtMin= 0
UNET MaxCRTS= 0
UNET WFStab= 0
UNET SFStab= 0
UNET WFX= 1
UNET SFX= 1
UNET Gravity=32.174
UNET 1D Methodology=Finite Difference
UNET DSS MLevel= 1
UNET Pardiso=0
UNET DZMax Abort= 0
UNET Use Existing IB Tables= 0
UNET Froude Reduction=False
UNET Froude Limit= 0
UNET Froude Power= 0
UNET D1 Cores= 0
UNET WindReference=Eulerian
UNET WindDragFormulation=Hsu (1988)
UNET D2 Coriolis=0
UNET D2 Cores= 0
UNET D2 Theta= 1
UNET D2 Theta Warmup= 1
UNET D2 Z Tol= 0.01
UNET D2 Volume Tol= 0.01
UNET D2 Max Iterations= 20
UNET D2 Equation= 0
UNET D2 RampUpFraction=0.1
UNET D2 TimeSlices= 1
UNET D2 Turbulence Formulation=Non-Conservative (original)
UNET D2 Eddy Viscosity=0.3
UNET D2 Transverse Eddy Viscosity=0.1
UNET D2 Smagorinsky Mixing=0
UNET D2 BCVolumeCheck=0
UNET D2 Cores=0
UNET D2 SolverType=PARDISO (Direct)
UNET D2 Minimum Iterations= 2147483647
UNET D2 Maximum Iterations= 2147483647
UNET D2 Restart Number= 10
UNET D2 Relaxation Coeff=1.3
UNET D2 SOR Precondition Iterations= 10
UNET D2 ILUT Maximum Fill= 8
UNET D2 ILUT Tolerance=1E-08
UNET D1D2 MaxIter= 0
UNET D1D2 ZTol=0.01
UNET D1D2 QTol=0.1
UNET D1D2 MinQTol=1
DSS File=dss
Write IC File= 0
Write IC File at Fixed DateTime=0
Write IC File at Sim End=0
Echo Input=False
Echo Parameters=False
Echo Output=False
Write Detailed= 0
HDF Write Warmup=0
HDF Write Time Slices=0
HDF Flush=0
HDF Compression= 1
HDF Chunk Size= 1
HDF Spatial Parts= 1
HDF Use Max Rows=0
HDF Fixed Rows= 1
Calibration Method= 0
Calibration Iterations= 20
Calibration Max Change=0.05
Calibration Tolerance=0.2
Calibration Maximum=1.5
Calibration Minimum=0.5
Calibration Optimization Method= 1
WQ AD Non Conservative
WQ ULTIMATE=-1
WQ Max Comp Step=1HOUR
WQ Output Interval=15MIN
WQ Output Selected Increments= 0
WQ Output face flow=0
WQ Output face velocity=0
WQ Output face area=0
WQ Output face dispersion=0
WQ Output cell volume=0
WQ Output cell surface area=0
WQ Output cell continuity=0
WQ Output cumulative cell continuity=0
WQ Output face conc=0
WQ Output face dconc_dx=0
WQ Output face courant=0
WQ Output face peclet=0
WQ Output face adv mass=0
WQ Output face disp mass=0
WQ Output cell mass=0
WQ Output cell source sink temp=0
WQ Output nsm pathways=0
WQ Output nsm derived pathways=0
WQ Create Restart=0
WQ Fixed Restart=0
WQ System Summary=0
WQ Write To DSS=0
Sorting and Armoring Iterations= 10
XS Update Threshold= 0.02
Bed Roughness Predictor= 0
Hydraulics Update Threshold= 0.02
Energy Slope Method= 1
Volume Change Method= 1
Sediment Retention Method= 0
Sediment TS Multiplier= 1
Warm Up Method= 0
XS Weighting Method= 0
Number of US Weighted Cross Sections= 1
Number of DS Weighted Cross Sections= 1
Upstream XS Weight=0
Main XS Weight=1
Downstream XS Weight=0
Number of DS XS's Weighted with US Boundary= 1
Upstream Boundary Weight= 1
Weight of XSs Associated with US Boundary= 0
Number of US XS's Weighted with DS Boundary= 1
Downstream Boundary Weight= 0.5
Weight of XSs Associated with DS Boundary= 0.5
Percentile Method= 0
Sediment Output Level= 3
Mass or Volume Output= 0
Output Increment Type= 1
Profile and TS Output Increment= 1
Transport Output Increment 1
XS Output Flag= 0
XS Output Increment= 10
Read HDF5 Sediment Hotstart= 0
Sediment Hotstart Type= 0
Write Gradation File= 0
Read Gradation Hotstart= 0
Write HDF5 File= 1
Write Binary Output= 1
Write DSS Sediment File= 0
DSS Sediment Output Type= 1
SV Curve= 0
Specific Gage Flag= 0
Subcell Erosion Methods= 0
Subcell Deposition Methods= 0
Advection Scheme= 1
Matrix Solver= 0
Implicit Weighting Factor= 1
Maximum Outer Loop Convergence Iterations= 5
Convergence Maximum Absolute= 0.001
Convergence RMSE= 0.0001
Grain Fractions Max Abs Error= 0.001
Max Subgrid Regions= 1
Max Subgrid Length Scale= 3.402823E+38
Initial Layer Thickness= 3.402823E+38
Min Layer Thickness= 3.402823E+38
Max Layer Thickness= 3.402823E+38
Number of Layers= 5

--- LAURELRN3.f01 (steady flow) ---

Flow Title=Flow
Program Version=6.10
Number of Profiles= 6
Profile Names=01pct,10pct,04pct,02pct,0_2pct,01plus
River Rch & RM=LAURELRN3,Main            ,8318
     658     350     464     558     917     973
River Rch & RM=LAURELRN3,Main            ,4709
     737     393     520     625    1020    1090
Boundary for River Rch & Prof#=LAURELRN3,Main            , 1
Up Type= 0
Dn Type= 3
Dn Slope=0.01771
Boundary for River Rch & Prof#=LAURELRN3,Main            , 2
Up Type= 0
Dn Type= 3
Dn Slope=0.01771
Boundary for River Rch & Prof#=LAURELRN3,Main            , 3
Up Type= 0
Dn Type= 3
Dn Slope=0.01771
Boundary for River Rch & Prof#=LAURELRN3,Main            , 4
Up Type= 0
Dn Type= 3
Dn Slope=0.01771
Boundary for River Rch & Prof#=LAURELRN3,Main            , 5
Up Type= 0
Dn Type= 3
Dn Slope=0.01771
Boundary for River Rch & Prof#=LAURELRN3,Main            , 6
Up Type= 0
Dn Type= 3
Dn Slope=0.01771
DSS Import GetInterval= 0
DSS Import GetPeak= 0
DSS Import FillOption= 0

--- LAURELRN3.g01 (geometry) ---

Geom Title=Geometry
Program Version=6.10

River Reach=LAURELRN3       ,Main
Reach XY= 30
 2249547.5404125475728.631839472      2249720.69      475631.294
     2249726.302      475496.512     2249830.667       475419.36
     2249872.205      475158.8352249792.56115418474853.134746139
     2249648.356      474552.487     2249641.549      474273.593
     2249488.676      474100.546     2249522.722      473967.423
     2249475.855      473484.819     2249545.314        473109.9
     2249459.582      473019.621     2249519.507      472887.843
     2249457.324      472489.692     2249533.692      472341.278
     2249459.316      471976.105      2249572.66      471846.089
     2249557.546      471629.031     2249865.606      471073.176
     2249877.665      470976.125 2249776.6694785470728.284117882
2249817.07849798      470615.826     2250066.416      470455.649
     2250261.468      470215.382     2250325.626      470062.566
     2250325.338      469910.361     2250709.014      469158.067
     2250899.511      468920.866     2250891.613      468428.798

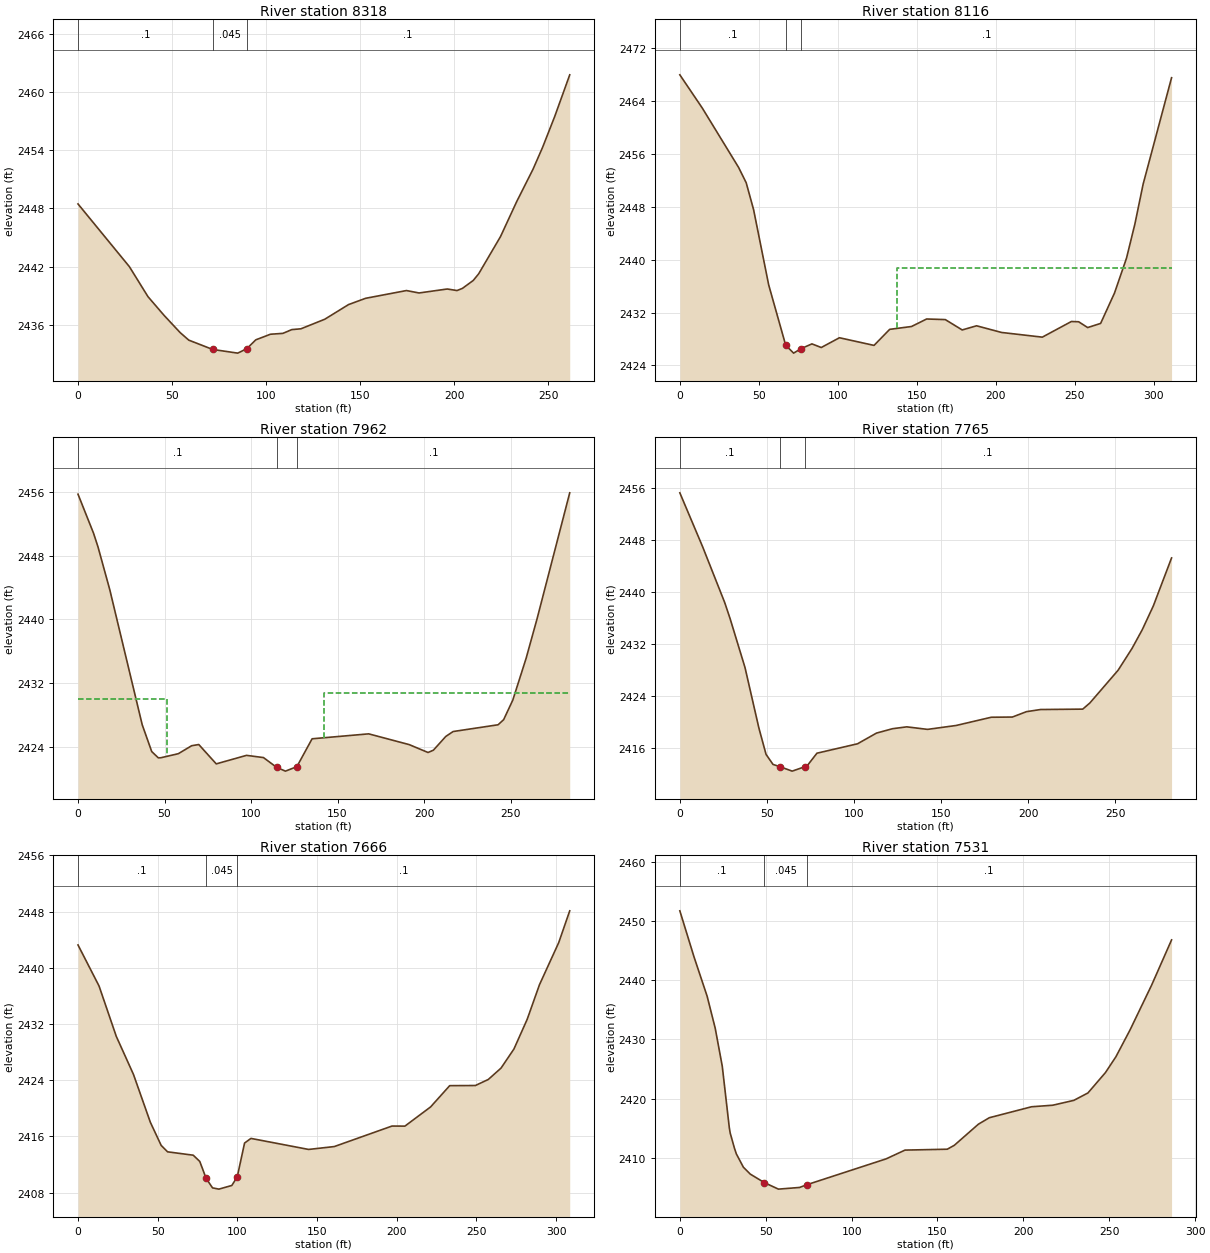
Type RM Length L Ch R = 1 ,8318    ,201.6,201.9,206.9
XS GIS Cut Line= 2
2249614.87979942  475769.77133662249397.13183053475625.153817642
#Sta/Elev= 30
       0 2448.46    27.3 2441.99    37.2 2438.89    45.7 2436.97    54.3 2435.18
    58.9  2434.4    71.6 2433.44    84.9 2433.06    89.7 2433.51    94.5 2434.43
   102.3 2435.01   108.9  2435.1   113.7 2435.49   118.5 2435.57   131.2 2436.56
   143.8 2438.07   152.9 2438.72   174.6 2439.52   181.3 2439.27   196.3 2439.68
   201.5 2439.52   204.4 2439.75   210.1 2440.56     213 2441.25   224.6 2445.09
   233.2  2448.7   241.9 2452.05   246.9 2454.27   253.4 2457.48   261.4 2461.79
#Mann= 3 ,-1,0
       0      .1       0    71.6    .045       0    89.7      .1       0
Bank Sta=71.6,89.7
XS Rating Curve= 0 ,0
Exp/Cntr(USF)=0,0
Exp/Cntr=0.3,0.1

Type RM Length L Ch R = 1 ,8116    ,154.1,153.9,154.8
XS GIS Cut Line= 3
2249779.44557275475677.4907744792249648.13863395475592.877158041
2249530.59110819475491.932672731
#Sta/Elev= 30
       0 2468.01    14.2 2462.98    37.2 2453.98      42 2451.66    46.7 2447.57
    56.2 2436.22      67 2427.05      72 2425.8676.684562426.533    83.6 2427.26
    89.5 2426.71     101 2428.19   122.9 2427.03   132.8 2429.46   146.6 2429.89
   156.2 2431.03     168 2430.94   178.7 2429.37   187.8    2430   203.6 2428.99
   229.4 2428.28   247.8 2430.65   252.4 2430.61   258.1 2429.73   266.3 2430.36
   275.1 2434.97   282.7 2440.26     288 2445.43   293.2 2451.45   311.2 2467.57
#Mann= 3 ,-1,0
       0      .1       0      67    .045       076.68456      .1       0
#XS Ineff= 2 , 0
                          137.52         2438.74
Permanent Ineff=
       F       F
Bank Sta=67,76.68456
XS Rating Curve= 0 ,0
Exp/Cntr(USF)=0,0
Exp/Cntr=0.3,0.1

Type RM Length L Ch R = 1 ,7962    ,203.1,196.9,193.3
XS GIS Cut Line= 2
 2249835.9145301475551.2016772652249592.69415731475404.119086961
#Sta/Elev= 30
       0 2455.71       9  2450.8    11.6 2449.06    18.4 2443.69    37.1 2426.77
    42.6  2423.4    46.4 2422.61    47.9 2422.62      58 2423.13    65.7 2424.13
    69.8 2424.28    79.9 2421.85    97.4 2422.92   107.2 2422.64   114.9  2421.4
   119.9 2420.94   126.5  2421.5   135.3    2425     168 2425.62   191.4 2424.27
   202.3 2423.28   205.4 2423.57   212.6  2425.3   216.8 2425.91   242.8 2426.76
     246  2427.4   251.3 2429.86     259 2435.11   265.3 2440.05   284.2 2455.88
#Mann= 3 ,-1,0
       0      .1       0   114.9    .045       0   126.5      .1       0
#XS Ineff= 2 , 0
           51.21 2430.02  142.03         2430.79
Permanent Ineff=
       F       F
Bank Sta=114.9,126.5
XS Rating Curve= 0 ,0
Exp/Cntr(USF)=0,0
Exp/Cntr=0.3,0.1

Type RM Length L Ch R = 1 ,7765    ,100,99.6,98.9
XS GIS Cut Line= 2
2249913.15343227 475357.282731392249633.77867974475317.019899407
#Sta/Elev= 30
       0 2455.25    13.1 2446.93    25.7 2438.39    28.8 2435.92    37.4 2428.35
    45.4    2419    49.5 2414.96    53.5 2413.41    57.5 2413.06    64.5 2412.38
    71.6 2413.04    73.7 2413.41    78.7 2415.14     102 2416.59   112.9 2418.24
   122.2 2418.92   130.3  2419.2   142.2 2418.81   158.6 2419.41   178.8 2420.68
   190.9 2420.71     199 2421.54   207.1 2421.87   231.3 2421.93   235.4 2422.88
   251.6 2427.92   259.6 2431.28   265.5 2434.18   271.8 2437.81   282.3 2445.22
#Mann= 3 ,-1,0
       0      .1       0    57.5    .045       0    71.6      .1       0
Bank Sta=57.5,71.6
XS Rating Curve= 0 ,0
Exp/Cntr(USF)=0,0
Exp/Cntr=0.3,0.1

Type RM Length L Ch R = 1 ,7666    ,141.1,134.7,130.3
XS GIS Cut Line= 3
2249945.19935977475278.4004483222249909.04498003475254.571425311
2249645.28234602475226.633950058
#Sta/Elev= 30
       0 2443.26    13.2 2437.42      24 2430.26    34.8 2424.83    45.4 2418.01
    52.2 2414.72    56.2 2413.81    72.3 2413.33    76.4 2412.44    80.4 2410.02
    84.4 2408.68    88.4  2408.5    96.5 2409.02    99.9 2410.24   104.5 2415.06
   108.5 2415.72   144.7 2414.15   160.8 2414.56     197 2417.48   205.1 2417.47
   221.2  2420.2   233.2 2423.23   249.3 2423.25   257.4 2424.11   265.4 2425.73
   273.5 2428.45   281.8 2432.67   289.5 2437.59   301.6  2443.6   308.5 2448.12
#Mann= 3 ,-1,0
       0      .1       0    80.4    .045       0    99.9      .1       0
Bank Sta=80.4,99.9
XS Rating Curve= 0 ,0
Exp/Cntr(USF)=0,0
Exp/Cntr=0.3,0.1

Type RM Length L Ch R = 1 ,7531    ,140.5,139.9,139.6
XS GIS Cut Line= 2
2249928.28289471475102.4197710272249648.56910781475163.363785514
#Sta/Elev= 30
       0 2451.73     8.3 2443.91    15.9  2437.3    20.6  2431.9    24.7 2425.49
    28.8 2415.11    29.3 2414.22    31.8 2411.64    32.9 2410.68      37 2408.43
      41 2407.27    49.2 2405.83    57.4 2404.73    69.7 2405.01    73.8 2405.46
   120.1 2409.84   131.1 2411.32   155.7 2411.47   159.8 2412.13   173.8 2415.69
   180.2 2416.79   204.8 2418.64   217.1  2418.9   229.4 2419.72   237.6 2420.97
   247.8 2424.41   253.9 2427.09   262.1  2431.6   274.7 2439.19   286.3 2446.82
#Mann= 3 ,-1,0
       0      .1       0    49.2    .045       0    73.8      .1       0
Bank Sta=49.2,73.8
XS Rating Curve= 0 ,0
Exp/Cntr(USF)=0,0
Exp/Cntr=0.3,0.1

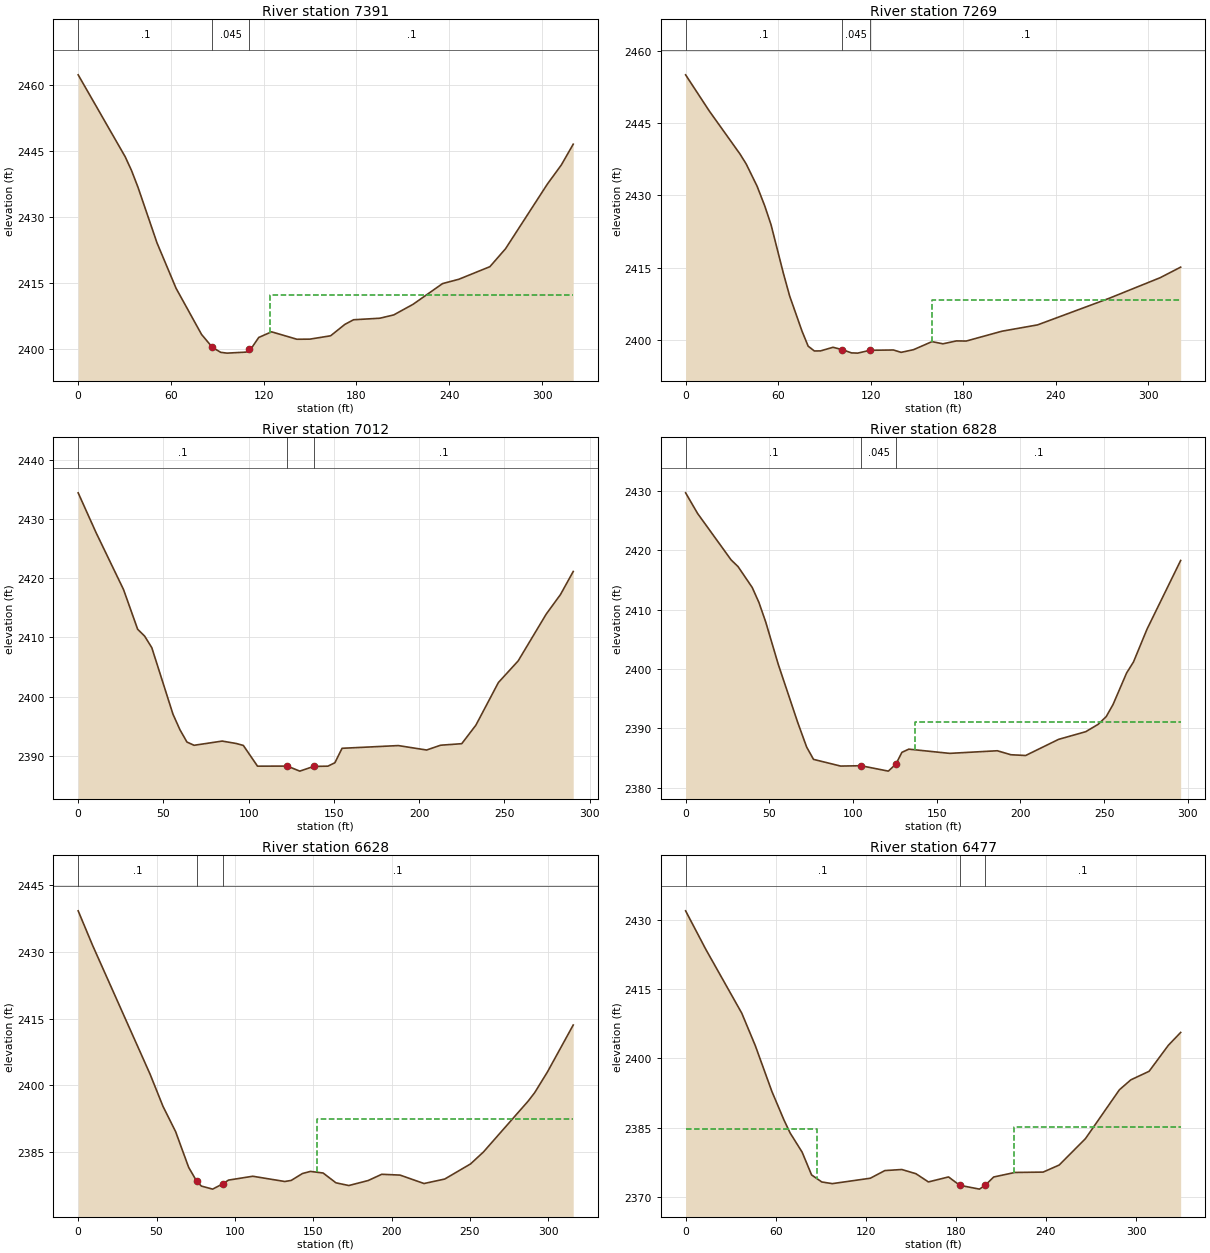
Type RM Length L Ch R = 1 ,7391    ,118.7,121.6,123.3
XS GIS Cut Line= 3
2249909.74760411474963.5621659912249765.47685519474998.457186991
2249613.34371076475078.218081417
#Sta/Elev= 30
       0 2462.21    30.4 2443.61    34.5 2440.48    38.7 2436.66      51 2424.02
    63.3 2413.73    79.8 2403.23    86.8 2400.29    92.2 2399.16    96.3 2398.98
   108.6 2399.21   110.72399.835   112.7 2400.43   116.8 2402.54   125.1 2403.82
   141.5 2402.13   149.9 2402.16   163.3 2402.92   172.5 2405.51   178.1 2406.56
   195.1 2406.91   204.1 2407.66   216.6 2410.07   235.7 2414.78   246.2 2415.76
   266.3 2418.62   276.4 2422.69   303.5  2437.4   312.5 2441.73   320.2 2446.45
#Mann= 3 ,-1,0
       0      .1       0    86.8    .045       0   110.7      .1       0
#XS Ineff= 2 , 0
                          123.99         2412.14
Permanent Ineff=
       F       F
Bank Sta=86.8,110.7
XS Rating Curve= 0 ,0
Exp/Cntr(USF)=0,0
Exp/Cntr=0.3,0.1

Type RM Length L Ch R = 1 ,7269    ,257.7,257.5,254.4
XS GIS Cut Line= 3
2249907.36344356474858.0190084482249745.10075689474872.687476804
2249665.48693492475009.352878698
#Sta/Elev= 30
       0 2454.98    15.3 2447.52    35.3 2438.57    39.3 2436.52    46.4 2431.89
    51.4 2427.77    55.4 2423.95    63.4  2413.9    67.5 2409.16    75.5  2401.9
    79.5 2398.78    83.5 2397.79    87.5  2397.8    95.6 2398.55   101.6 2398.06
   107.6 2397.39   111.6 2397.34   119.7 2397.93   134.8 2397.99   139.8  2397.5
   147.8 2398.05   159.8 2399.72   166.9 2399.27   175.7 2399.87     182 2399.84
   205.2 2401.88   228.3 2403.19   274.6 2408.68   307.8 2412.96   321.1 2415.15
#Mann= 3 ,-1,0
       0      .1       0   101.6    .045       0   119.7      .1       0
#XS Ineff= 2 , 0
                           159.5         2408.27
Permanent Ineff=
       F       F
Bank Sta=101.6,119.7
XS Rating Curve= 0 ,0
Exp/Cntr(USF)=0,0
Exp/Cntr=0.3,0.1

Type RM Length L Ch R = 1 ,7012    ,182.7,183.9,184.9
XS GIS Cut Line= 2
2249805.94140313474622.275002664 2249524.9232697474695.405452592
#Sta/Elev= 30
       0 2434.45    10.4 2427.78    26.6  2418.1    34.9 2411.38      39 2410.22
    43.2 2408.26    55.6 2397.03    59.7 2394.39    63.8 2392.31      68 2391.76
    84.5 2392.47    92.8 2392.06    96.9 2391.73   105.2 2388.23   122.7 2388.24
     130 2387.39   138.2 2388.19   146.5 2388.23   150.6 2388.81   154.8 2391.25
   187.8 2391.71   204.4 2390.96   212.6 2391.77     225 2392.03   233.3 2395.16
   246.5 2402.37   258.1 2406.03   274.6 2413.96   282.9 2417.24   290.4 2421.15
#Mann= 3 ,-1,0
       0      .1       0   122.7    .045       0   138.2      .1       0
Bank Sta=122.7,138.2
XS Rating Curve= 0 ,0
Exp/Cntr(USF)=0,0
Exp/Cntr=0.3,0.1

Type RM Length L Ch R = 1 ,6828    ,201.5,200.5,202
XS GIS Cut Line= 2
2249751.28041389474455.8883092472249460.40199508474509.298188407
#Sta/Elev= 30
       0 2429.65     7.2 2426.16    27.2 2418.35    31.3 2417.24    39.8 2413.71
    43.8 2411.19    47.9 2407.86    55.3 2400.81      67 2390.96    72.3 2386.84
    76.4 2384.77    92.6 2383.64   104.8  2383.7   121.1 2382.79   125.62383.972
   129.2 2385.95   133.3 2386.49   157.7 2385.78   186.2 2386.22   194.3 2385.55
   203.1 2385.42   222.8 2388.14     239 2389.43   246.4 2390.67   251.2 2391.96
   255.3    2394   263.4 2399.31   267.5 2401.16   275.6 2406.69   295.7 2418.26
#Mann= 3 ,-1,0
       0      .1       0   104.8    .045       0   125.6      .1       0
#XS Ineff= 2 , 0
                          137.04          2391.1
Permanent Ineff=
       F       F
Bank Sta=104.8,125.6
XS Rating Curve= 0 ,0
Exp/Cntr(USF)=0,0
Exp/Cntr=0.3,0.1

Type RM Length L Ch R = 1 ,6628    ,159.2,150.3,149.9
XS GIS Cut Line= 2
2249729.09477178474260.325982474 2249420.1391631474326.061218364
#Sta/Elev= 30
       0 2439.29     9.1  2431.6    45.9  2402.5    54.1 2395.29    62.2 2389.56
    70.5 2381.54    75.7 2378.36    78.6 2377.32    85.8 2376.63    92.5 2377.86
    95.9 2378.66   111.4 2379.53   131.8 2378.35   135.9 2378.58   143.1 2380.14
   148.2 2380.62   156.3 2380.26   164.5 2378.05   172.7 2377.44     185 2378.56
   193.7 2379.97   205.4 2379.79   220.7 2377.89   233.9  2378.9   250.4 2382.31
   258.6 2384.99   287.2 2396.47   291.3 2398.35   299.5 2403.05   315.9 2413.58
#Mann= 3 ,-1,0
       0      .1       0    75.7    .045       0    92.5      .1       0
#XS Ineff= 2 , 0
                          152.33         2392.37
Permanent Ineff=
       F       F
Bank Sta=75.7,92.5
XS Rating Curve= 0 ,0
Exp/Cntr(USF)=0,0
Exp/Cntr=0.3,0.1

Type RM Length L Ch R = 1 ,6477    ,96.2,98.5,103
XS GIS Cut Line= 4
2249685.47365114474101.9731123942249607.09126101474108.896979384
 2249572.7586563474157.9518809222249410.27887771474258.682601576
#Sta/Elev= 30
       0 2431.97    13.4 2423.66    37.4  2409.8    46.4 2402.78    57.5 2392.81
    65.6 2386.59    69.6 2383.85    77.6 2379.69    83.9 2374.76    90.7 2373.23
    97.7 2372.87     123 2374.04   132.7  2375.7     144 2375.93   153.4 2375.02
   161.7 2373.24   175.1 2374.32   182.6 2372.51   195.7 2371.68   199.4 2372.48
   205.2 2374.31   219.3 2375.29   238.1 2375.37   248.8  2376.9   266.3 2382.62
   288.9  2393.2   296.5 2395.35   308.7 2397.21   321.5 2402.84   329.7 2405.62
#Mann= 3 ,-1,0
       0      .1       0   182.6    .045       0   199.4      .1       0
#XS Ineff= 2 , 0
           87.79 2384.68  218.68         2385.08
Permanent Ineff=
       F       F
Bank Sta=182.6,199.4
XS Rating Curve= 0 ,0
Exp/Cntr(USF)=0,0
Exp/Cntr=0.3,0.1

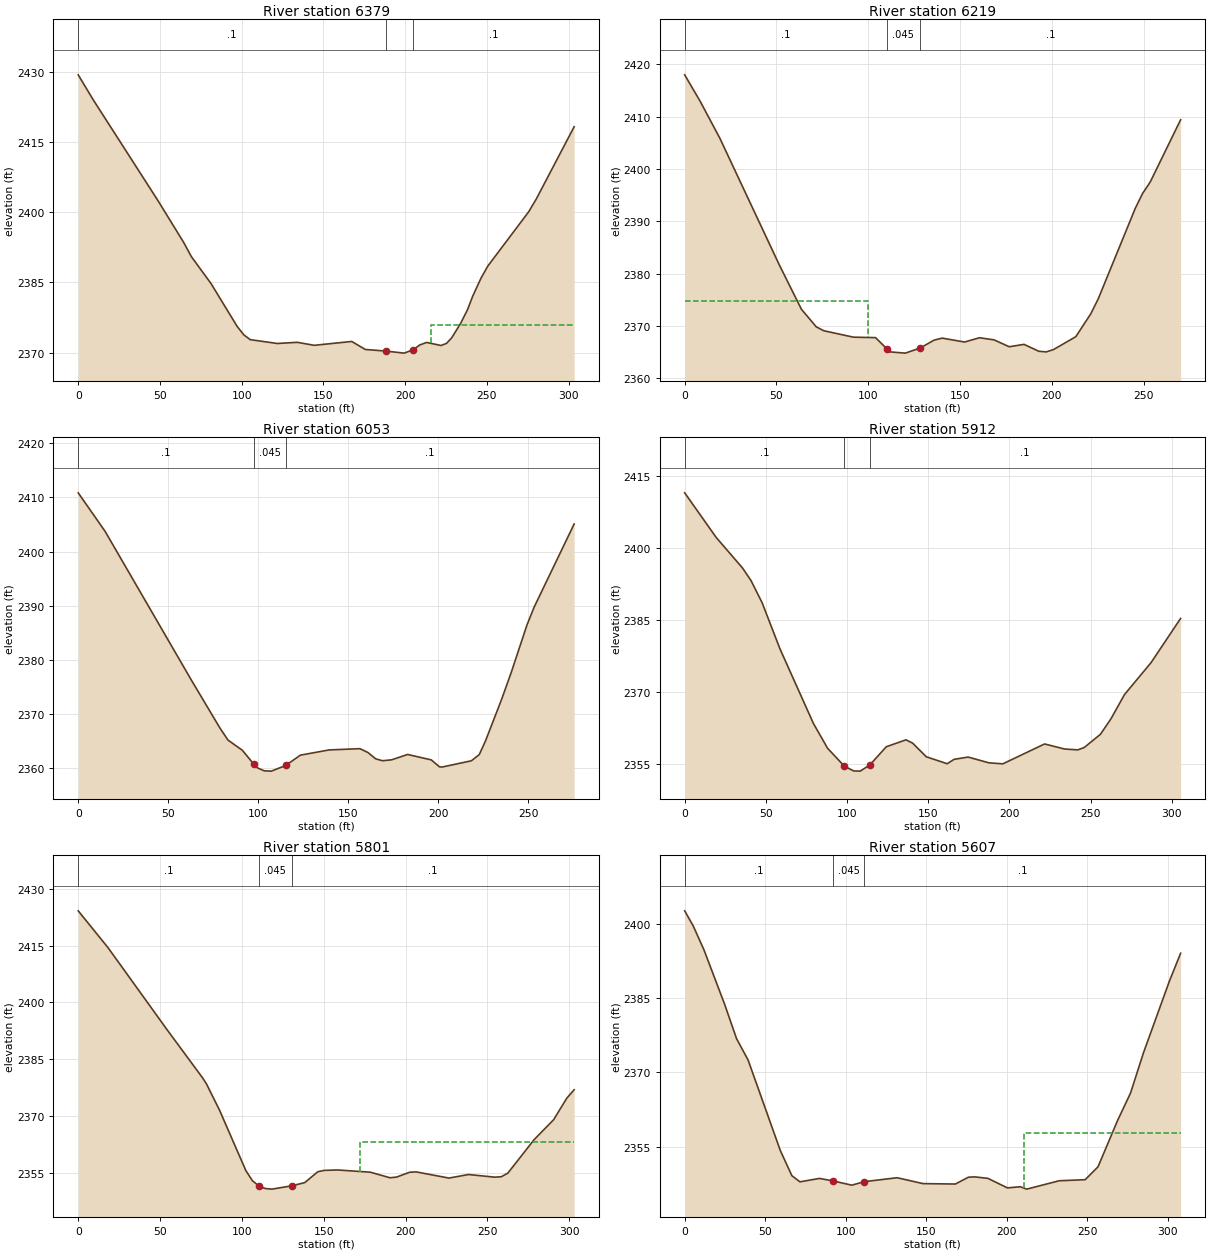
Type RM Length L Ch R = 1 ,6379    ,161.1,159.3,163.7
XS GIS Cut Line= 3
2249677.38191963474072.1740436162249562.92191919 474075.04223957
2249381.43414322474127.106809977
#Sta/Elev= 30
       0 2429.36     9.2 2424.01      49 2402.36    64.6 2393.49    69.2 2390.52
    81.2 2384.78    97.2 2375.61   101.2 2373.83   105.2 2372.78   121.7 2371.96
     134 2372.21   144.3 2371.57   167.3 2372.39   175.6 2370.68   188.1 2370.34
   199.3  2369.9204.61732370.576   208.9 2371.65   213.1 2372.18   221.9 2371.53
   225.2 2371.97   228.4 2373.16   233.9 2376.27   238.1 2379.19   241.3  2382.1
   246.4 2385.96   250.5  2388.5   275.5  2400.1   280.1  2402.8   303.3 2418.27
#Mann= 3 ,-1,0
       0      .1       0   188.1    .045       0204.6173      .1       0
#XS Ineff= 2 , 0
                          215.52         2375.83
Permanent Ineff=
       F       F
Bank Sta=188.1,204.6173
XS Rating Curve= 0 ,0
Exp/Cntr(USF)=0,0
Exp/Cntr=0.3,0.1

Type RM Length L Ch R = 1 ,6219    ,165.3,165.9,166.6
XS GIS Cut Line= 2
2249639.16531713473925.3866958262249371.65942663473963.732250095
#Sta/Elev= 30
       0 2418.01     8.5 2412.92    19.2 2405.87    51.5 2381.73    63.6 2373.22
    71.7 2369.85    75.8 2369.11    91.9 2367.88     104 2367.79  110.032365.692
   112.1 2365.06   120.2 2364.83   128.3  2365.8   135.8  2367.3   140.3  2367.7
   152.5 2366.95   160.6 2367.77   168.6 2367.36   176.8 2366.05   184.9  2366.5
   192.9 2365.19     197 2365.06     201 2365.52   213.1 2367.97   221.2 2372.31
   225.3 2375.18   245.5  2392.5   249.5 2395.35   253.6  2397.5   270.2 2409.42
#Mann= 3 ,-1,0
       0      .1       0  110.03    .045       0   128.3      .1       0
#XS Ineff= 2 , 0
             100 2374.71
Permanent Ineff=
       F       F
Bank Sta=110.03,128.3
XS Rating Curve= 0 ,0
Exp/Cntr(USF)=0,0
Exp/Cntr=0.3,0.1

Type RM Length L Ch R = 1 ,6053    ,141.7,141.4,140.8
XS GIS Cut Line= 3
2249598.99378408473770.1784999742249453.74329998473783.797032363
2249336.50336377473839.007684042
#Sta/Elev= 30
       0 2410.85    14.9 2403.75    63.1  2376.1    78.8 2367.34    83.2 2365.15
    91.2 2363.2697.680812360.641    99.3 2360.06   103.3 2359.47   107.3 2359.41
   115.3 2360.46   123.4 2362.36   139.4 2363.33   156.5 2363.56   160.9 2362.86
   165.3 2361.67   169.1 2361.33   174.1  2361.5     183 2362.49   196.1 2361.49
   200.7  2360.2   202.2 2360.17   218.4 2361.32   222.8 2362.47   226.3 2365.03
   235.3 2372.76   240.5  2377.6   249.3 2386.43   253.3 2389.74   275.5 2405.09
#Mann= 3 ,-1,0
       0      .1       097.68081    .045       0   115.3      .1       0
Bank Sta=97.68081,115.3
XS Rating Curve= 0 ,0
Exp/Cntr(USF)=0,0
Exp/Cntr=0.3,0.1

Type RM Length L Ch R = 1 ,5912    ,109,111.1,113.4
XS GIS Cut Line= 4
 2249583.4729645473626.839166158 2249442.3607899473644.361283835
2249368.94359986473615.9050086252249286.41949262473634.440000298
#Sta/Elev= 30
       0 2411.59    19.4  2402.3    35.6 2395.94    40.9 2393.29    47.7 2388.69
    58.8    2379    79.3 2363.54      88 2358.38    98.3 2354.65   104.1 2353.64
   108.1  2353.6  113.962354.853   124.2 2358.68   136.3 2360.12   140.4 2359.44
   148.8  2356.6   161.7 2355.14     166 2356.06   174.6 2356.53   187.4 2355.33
     196 2355.12   221.7 2359.26     234 2358.21   242.2 2358.03   246.1 2358.52
   256.1 2361.27   262.6 2364.51   270.9 2369.54   287.3 2376.21   305.5 2385.42
#Mann= 3 ,-1,0
       0      .1       0    98.3    .045       0  113.96      .1       0
Bank Sta=98.3,113.96
XS Rating Curve= 0 ,0
Exp/Cntr(USF)=0,0
Exp/Cntr=0.3,0.1

Type RM Length L Ch R = 1 ,5801    ,192.7,193.7,194.9
XS GIS Cut Line= 2
2249594.48772488473533.7842525262249291.73105507473521.737900482
#Sta/Elev= 30
       0 2424.16    18.2 2414.44    54.4  2392.7      76 2380.04    78.4 2378.42
    86.4 2371.46   102.4 2355.58   106.4  2352.9   110.4 2351.47   114.3 2350.82
   118.4 2350.66   130.4 2351.53   138.4 2352.38   146.4 2355.26   150.4 2355.61
   158.4 2355.72   178.5 2355.13   190.5 2353.66   194.5 2353.84   202.5 2355.12
   206.5 2355.21   226.5 2353.58   238.5 2354.52   254.5 2353.82   258.5 2353.93
   262.5 2354.89   278.5 2363.71   290.5 2369.01   298.5 2374.68     303 2376.91
#Mann= 3 ,-1,0
       0      .1       0   110.4    .045       0   130.4      .1       0
#XS Ineff= 2 , 0
                          172.46         2363.17
Permanent Ineff=
       F       F
Bank Sta=110.4,130.4
XS Rating Curve= 0 ,0
Exp/Cntr(USF)=0,0
Exp/Cntr=0.3,0.1

Type RM Length L Ch R = 1 ,5607    ,108.1,109.7,109.3
XS GIS Cut Line= 3
2249580.08916192473376.3031713582249532.28261956473341.017390098
2249285.28215074473312.561114888
#Sta/Elev= 30
       0 2402.61     5.3 2399.57      12 2394.72    24.8 2383.78    32.2 2376.85
    39.4 2372.51    59.4 2354.27    66.6 2349.18    71.6 2347.94    83.7 2348.63
    92.4 2348.11   103.8 2347.27   111.7 2347.98     132 2348.77   148.1 2347.58
   168.2  2347.5   176.3 2348.88   180.3 2348.94   188.4 2348.64   200.5 2346.72
   208.5 2346.95   212.5 2346.47   232.7 2348.16   248.8 2348.37   256.8 2350.98
   268.9 2360.29     277 2365.86     285 2373.95   301.1  2388.4   308.1 2394.05
#Mann= 3 ,-1,0
       0      .1       0    92.4    .045       0   111.7      .1       0
#XS Ineff= 2 , 0
                          211.05         2357.76
Permanent Ineff=
       F       F
Bank Sta=92.4,111.7
XS Rating Curve= 0 ,0
Exp/Cntr(USF)=0,0
Exp/Cntr=0.3,0.1

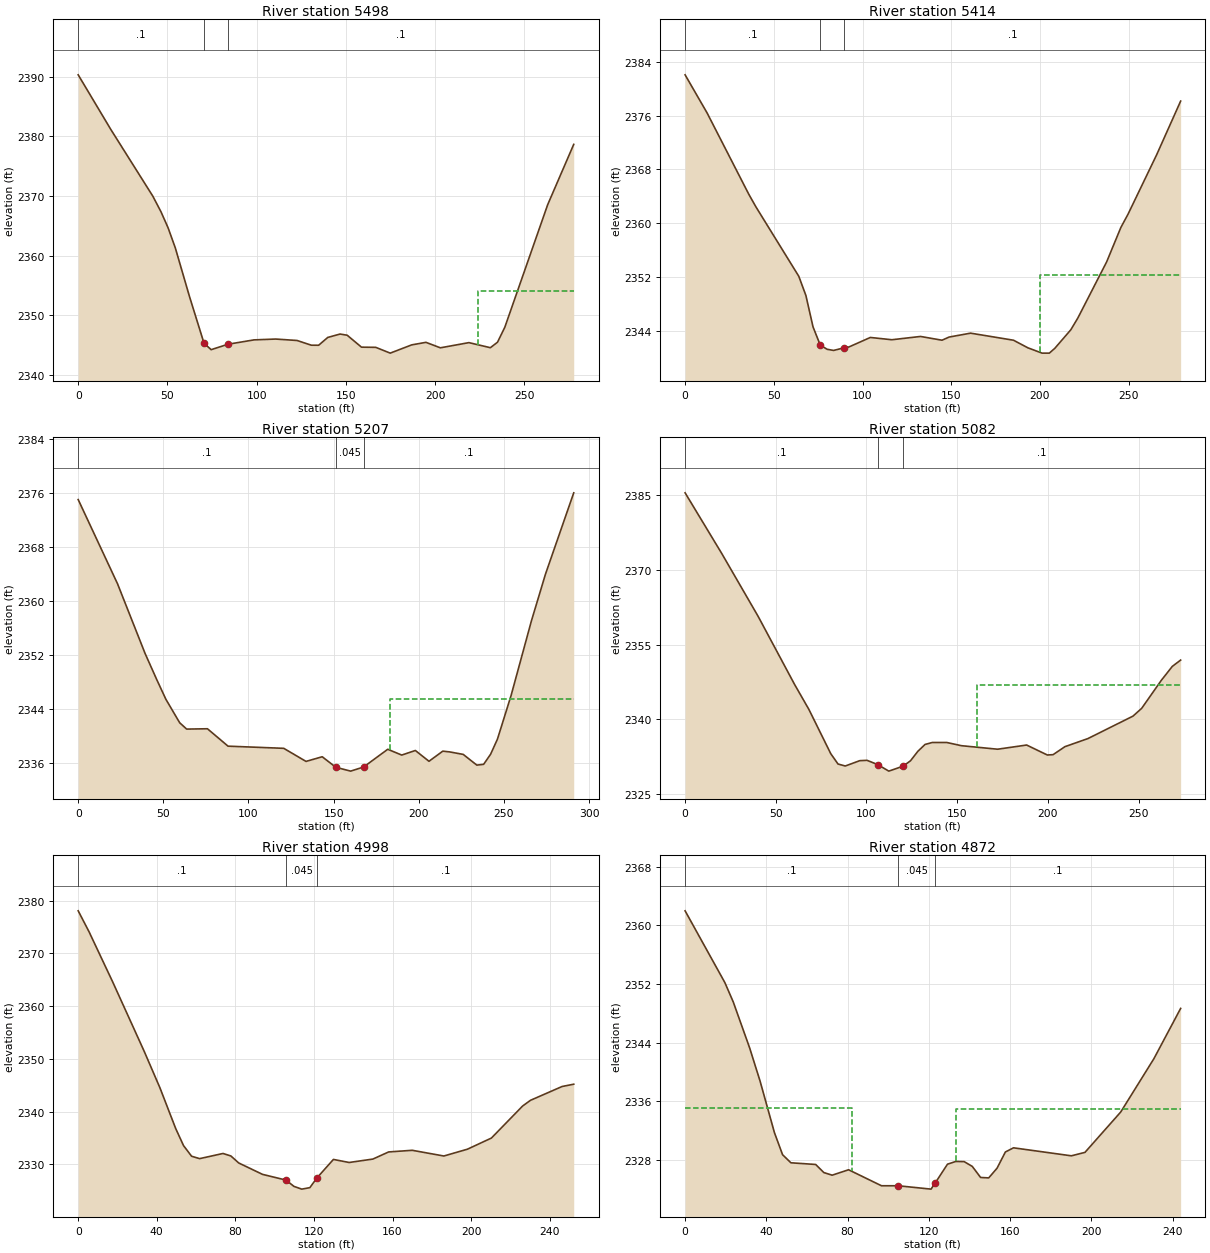
Type RM Length L Ch R = 1 ,5498    ,82.4,83.3,83.6
XS GIS Cut Line= 2
  2249610.429025473245.0065671642249333.61590625473223.698272873
#Sta/Elev= 30
       0 2390.32    18.3 2381.15    41.8 2369.98    46.4 2367.35    50.4 2364.64
    54.4 2361.31    62.4  2353.1    70.5 2345.31    74.5 2344.24    83.9 2345.15
    98.5 2345.88   110.6 2346.02   122.6 2345.78   130.6 2344.99   134.7 2344.98
   139.8 2346.29   146.7 2346.86   150.7 2346.66   158.7 2344.66   166.7 2344.63
   174.8 2343.66   186.8 2345.04   194.8 2345.47   202.9 2344.55   218.9 2345.42
   230.9 2344.57   234.9 2345.49     239    2348     263 2368.54   277.6 2378.66
#Mann= 3 ,-1,0
       0      .1       0    70.5    .045       0    83.9      .1       0
#XS Ineff= 2 , 0
                          223.75         2354.05
Permanent Ineff=
       F       F
Bank Sta=70.5,83.9
XS Rating Curve= 0 ,0
Exp/Cntr(USF)=0,0
Exp/Cntr=0.3,0.1

Type RM Length L Ch R = 1 ,5414    ,197.6,207,207.8
XS GIS Cut Line= 2
2249619.68450481473167.6038507742249342.79957302473130.967326558
#Sta/Elev= 30
       0 2382.05    12.4 2376.38    35.8 2364.34    39.9 2362.42    64.1 2352.08
    68.1 2349.22    72.1 2344.57    76.2 2341.84    80.1 2341.23    83.7 2341.06
    89.6 2341.45    92.3 2341.57   104.4 2342.99   116.5 2342.65   132.7 2343.14
   144.8 2342.58   148.8 2343.05   160.9 2343.63   185.1 2342.58   193.2 2341.45
   201.2 2340.66   205.3 2340.66   208.4 2341.38   217.4 2344.13   221.4  2345.9
   237.6 2354.23   245.6 2359.34   249.7 2361.35   265.8 2370.17   279.3 2378.14
#Mann= 3 ,-1,0
       0      .1       0    76.2    .045       0    89.6      .1       0
#XS Ineff= 2 , 0
                             200         2352.35
Permanent Ineff=
       F       F
Bank Sta=76.2,89.6
XS Rating Curve= 0 ,0
Exp/Cntr(USF)=0,0
Exp/Cntr=0.3,0.1

Type RM Length L Ch R = 1 ,5207    ,129.2,125.6,119.5
XS GIS Cut Line= 4
2249618.96094834472996.1529324022249502.68809335473016.046727202
 2249442.9299154472989.8669540092249335.47246846472998.669936673
#Sta/Elev= 30
       0 2375.08    23.1  2362.6    39.3 2352.26    46.2 2348.36    51.5 2345.48
    59.6    2342    63.7 2341.06    75.9 2341.11      88 2338.53   120.7 2338.21
   133.8 2336.27   143.3 2336.96   151.3  2335.4     160 2334.83   167.6 2335.44
   181.8 2338.07     190 2337.21     198 2337.89     206 2336.29   214.1 2337.79
   218.1 2337.68   226.1 2337.31   234.1 2335.72   238.1 2335.84   242.2 2337.34
   246.2 2339.57   254.2 2346.03   266.2 2357.14   274.4 2364.02     291 2376.08
#Mann= 3 ,-1,0
       0      .1       0   151.3    .045       0   167.6      .1       0
#XS Ineff= 2 , 0
                          183.09         2345.59
Permanent Ineff=
       F       F
Bank Sta=151.3,167.6
XS Rating Curve= 0 ,0
Exp/Cntr(USF)=0,0
Exp/Cntr=0.3,0.1

Type RM Length L Ch R = 1 ,5082    ,84.4,83.5,82.8
XS GIS Cut Line= 3
 2249632.4487083472890.839116279 2249442.9299154472891.408241783
2249363.82147032472864.090217581
#Sta/Elev= 30
       0 2385.47    20.3 2373.23    40.3 2360.64    60.3 2347.03    68.3 2341.94
    80.3 2333.09    84.3 2331.01    88.3 2330.61    96.3 2331.68   100.3 2331.75
   106.3 2330.88   112.3 2329.58   120.3 2330.59   124.3 2331.67   128.3 2333.55
   132.3 2334.94   136.3 2335.33   144.3 2335.33   152.3 2334.69   172.3 2333.98
   188.3 2334.82   199.7 2332.82   202.9 2332.89   209.4 2334.49   222.1 2336.12
   246.9 2340.62   251.7 2342.18   262.6 2347.84   268.6 2350.61   273.2 2351.88
#Mann= 3 ,-1,0
       0      .1       0   106.3    .045       0   120.3      .1       0
#XS Ineff= 2 , 0
                          160.87          2346.8
Permanent Ineff=
       F       F
Bank Sta=106.3,120.3
XS Rating Curve= 0 ,0
Exp/Cntr(USF)=0,0
Exp/Cntr=0.3,0.1

Type RM Length L Ch R = 1 ,4998    ,127.5,126.6,125.1
XS GIS Cut Line= 2
2249617.65528716472800.3920428242249366.21800988472820.359120725
#Sta/Elev= 30
       0 2378.08     5.5 2374.13    17.5 2364.65    33.6 2351.44    41.6 2344.53
    49.6 2336.83    53.6 2333.58    57.7 2331.56    61.8  2331.1    73.7 2332.08
    77.7 2331.61    81.7 2330.28    93.8 2328.12   105.8 2327.03   109.8 2325.84
   113.8 2325.32   117.9  2325.6   121.52327.444   129.9 2330.95   137.9 2330.37
     150 2331.02     158 2332.37     170 2332.68   186.1  2331.6   198.1 2332.89
   210.3    2335   226.2 2341.08   230.2 2342.16   246.3 2344.78   252.2 2345.21
#Mann= 3 ,-1,0
       0      .1       0   105.8    .045       0   121.5      .1       0
Bank Sta=105.8,121.5
XS Rating Curve= 0 ,0
Exp/Cntr(USF)=0,0
Exp/Cntr=0.3,0.1

Type RM Length L Ch R = 1 ,4872    ,160.7,162.3,163.4
XS GIS Cut Line= 2
2249595.46964505472665.7991473392249355.12518882472707.951867353
#Sta/Elev= 30
       0 2361.98    19.6 2352.19    23.7 2349.57    31.8 2343.28    36.9 2338.79
      44 2331.74      48 2328.74    52.1 2327.64    64.3 2327.41    68.3 2326.31
    72.4 2325.95    80.5 2326.69    96.7 2324.51   104.9 2324.51   121.1 2324.05
     123 2324.82   129.2 2327.45   133.3 2327.82   137.4  2327.8   141.4 2327.15
   145.5 2325.64   149.5 2325.58   153.6  2326.9   157.7 2329.11   161.7 2329.68
   190.2 2328.59   196.9 2329.06   214.5 2334.56   230.8 2341.81     244 2348.68
#Mann= 3 ,-1,0
       0      .1       0   104.9    .045       0     123      .1       0
#XS Ineff= 2 , 0
           82.13 2335.12  133.31            2335
Permanent Ineff=
       F       F
Bank Sta=104.9,123
XS Rating Curve= 0 ,0
Exp/Cntr(USF)=0,0
Exp/Cntr=0.3,0.1

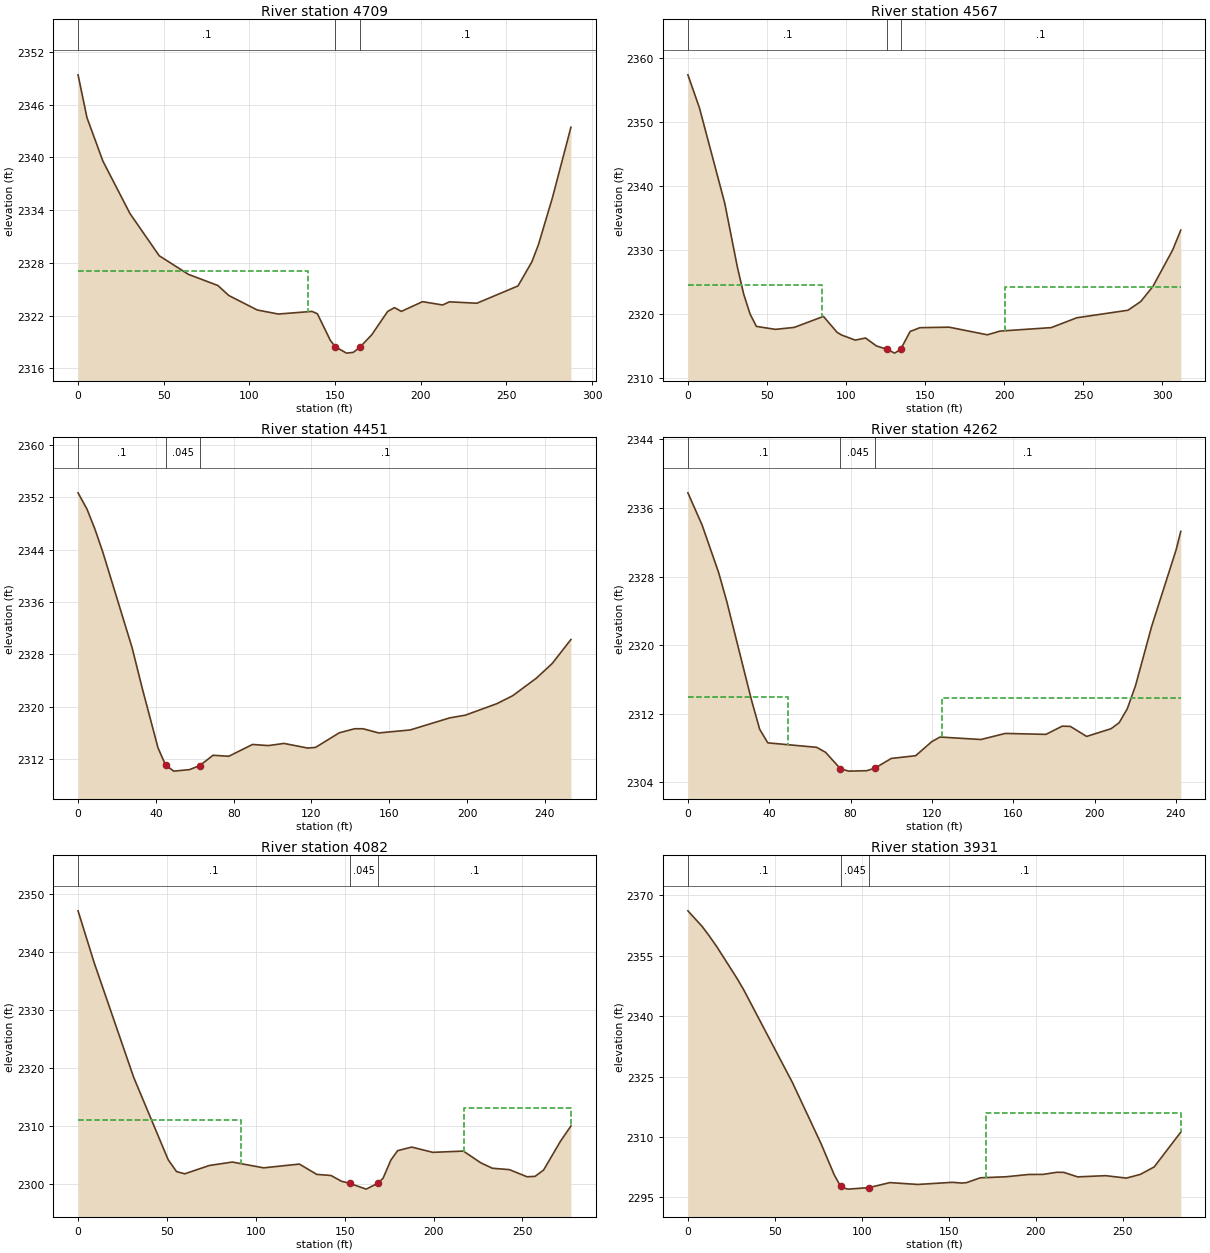
Type RM Length L Ch R = 1 ,4709    ,130.1,141.9,150.6
XS GIS Cut Line= 3
2249600.98708667472571.3584888112249511.43338895472523.971181165
2249325.31258145472534.436938911
#Sta/Elev= 30
       0  2349.4     5.2 2344.53    14.5 2339.58    30.3 2333.61    47.4  2328.8
    64.5 2326.68    81.6 2325.42      88 2324.28   104.6 2322.63   116.9 2322.17
   136.6 2322.47   139.7  2322.2   147.3 2319.16   150.2 2318.44   156.7 2317.72
   160.7 2317.81   164.7 2318.43   171.4  2319.8   180.7 2322.46   184.7  2322.9
   188.7 2322.47   201.1 2323.58   212.8  2323.2   216.8 2323.56   232.8  2323.4
   256.8 2325.37   264.9 2328.11   268.7 2330.05   276.9 2335.41   287.7 2343.44
#Mann= 3 ,-1,0
       0      .1       0   150.2    .045       0   164.7      .1       0
#XS Ineff= 2 , 0
           134.3 2327.12
Permanent Ineff=
       F       F
Bank Sta=150.2,164.7
XS Rating Curve= 0 ,0
Exp/Cntr(USF)=0,0
Exp/Cntr=0.3,0.1

Type RM Length L Ch R = 1 ,4567    ,131.5,116.1,106.3
XS GIS Cut Line= 4
 2249599.5148789472431.9229002652249518.05448196472433.262210905
2249471.38619061472367.8127779222249323.10085227472347.113107571
#Sta/Elev= 30
       0 2357.31     7.3 2352.16    23.3 2337.28    31.3 2327.29    35.3 2323.08
    39.3    2320    43.3 2318.06    55.3  2317.6    67.2  2317.9    85.7 2319.62
    94.3 2317.14    97.2 2316.71   105.8 2315.92   112.3 2316.25   119.2 2315.01
   125.8  2314.5   130.7 2313.89   134.5 2314.48   140.5 2317.27   146.7 2317.86
   165.1 2317.94   189.3 2316.75   197.4 2317.33   229.7 2317.87   245.9 2319.41
   278.2 2320.58   286.3 2321.94     294  2324.3   306.5    2330   311.6 2333.08
#Mann= 3 ,-1,0
       0      .1       0   125.8    .045       0   134.5      .1       0
#XS Ineff= 2 , 0
           84.54 2324.51  200.58         2324.15
Permanent Ineff=
       F       F
Bank Sta=125.8,134.5
XS Rating Curve= 0 ,0
Exp/Cntr(USF)=0,0
Exp/Cntr=0.3,0.1

Type RM Length L Ch R = 1 ,4451    ,188.8,189.4,190.6
XS GIS Cut Line= 2
2249580.67921697472285.685145804 2249330.7209825472327.098344415
#Sta/Elev= 30
       0 2352.68     4.6 2350.19     8.6  2347.2    12.7 2343.66    27.8 2329.02
    32.9 2322.96    41.1 2313.75      45 2311.11    49.2 2310.19    57.3 2310.42
    62.6 2311.04    69.4 2312.61    77.5 2312.46    89.7 2314.26    97.8 2314.09
   105.9 2314.42   118.1 2313.71   122.1 2313.81   134.3 2316.04   142.2 2316.66
   146.5 2316.66   154.6 2316.02   170.8 2316.48   191.1 2318.32   199.2 2318.74
   215.4  2320.5   223.5 2321.71   235.7  2324.4   243.8 2326.63   253.4 2330.29
#Mann= 3 ,-1,0
       0      .1       0      45    .045       0    62.6      .1       0
Bank Sta=45,62.6
XS Rating Curve= 0 ,0
Exp/Cntr(USF)=0,0
Exp/Cntr=0.3,0.1

Type RM Length L Ch R = 1 ,4262    ,172.4,180.2,187.6
XS GIS Cut Line= 4
2249567.08139271472118.8873233842249495.07291821472108.044837734
2249476.85468117472111.4056551432249325.85154883472106.427962871
#Sta/Elev= 30
       0 2337.77       7    2334    15.1 2328.48    19.1 2325.11    31.3 2313.56
    35.3 2310.18    39.3 2308.59    63.3 2308.07    67.7 2307.49      75 2305.57
    79.1 2305.29      88 2305.34      92 2305.64     100 2306.77     112 2307.09
     120 2308.74     124 2309.27   144.1 2308.98   156.1 2309.69   176.1 2309.58
   184.1 2310.54   188.1 2310.51   196.1 2309.34   208.1 2310.24   212.1 2310.94
   216.1 2312.57   220.1 2315.23   228.1  2322.2   240.1 2331.11   242.4 2333.27
#Mann= 3 ,-1,0
       0      .1       0      75    .045       0      92      .1       0
#XS Ineff= 2 , 0
           49.11 2313.99   124.8         2313.87
Permanent Ineff=
       F       F
Bank Sta=75,92
XS Rating Curve= 0 ,0
Exp/Cntr(USF)=0,0
Exp/Cntr=0.3,0.1

Type RM Length L Ch R = 1 ,4082    ,162,150.7,148
XS GIS Cut Line= 3
2249619.92627225472024.2769711922249457.56431767471928.845193193
 2249383.3101807 471879.84366684
#Sta/Elev= 30
       0 2347.18       9  2338.3    31.3 2318.47    50.7 2304.27    55.4 2302.23
      60 2301.84    73.9 2303.28    86.8 2303.87   104.4 2302.87   124.5 2303.52
   134.3 2301.74   142.3 2301.55   148.2 2300.56   152.8  2300.2   162.1  2299.2
   168.6  2300.2   171.6 2301.08     176 2304.21   179.8 2305.83   187.7 2306.45
   199.6 2305.54   216.8 2305.76   226.6 2303.73   233.1  2302.8   242.7 2302.56
   252.6 2301.33   257.1  2301.4   261.9 2302.48   271.5  2307.5   277.3 2310.08
#Mann= 3 ,-1,0
       0      .1       0   152.8    .045       0   168.6      .1       0
#XS Ineff= 2 , 0
           91.79 2311.08  217.39         2313.18
Permanent Ineff=
       F       F
Bank Sta=152.8,168.6
XS Rating Curve= 0 ,0
Exp/Cntr(USF)=0,0
Exp/Cntr=0.3,0.1

Type RM Length L Ch R = 1 ,3931    ,63.5,61.2,60.2
XS GIS Cut Line= 2
2249676.40535898471828.6767029682249392.94193668 471831.72542172
#Sta/Elev= 30
       0  2366.1     8.2 2362.23    12.2 2359.92    16.6 2357.23    28.2 2349.38
    32.2 2346.44    60.1 2323.53    76.6 2308.34    84.2 2300.59    87.8  2297.8
    88.2 2297.49    92.2 2297.07   104.2 2297.45   116.2 2298.69   132.2 2298.23
   152.2 2298.76   157.4 2298.58   160.2 2298.67   168.2 2299.88   182.8 2300.13
   196.2 2300.71   204.2 2300.72   212.2 2301.25   216.2 2301.23   224.2 2300.11
   240.2 2300.41   252.2 2299.81   260.2 2300.72   268.2 2302.57   283.5 2311.21
#Mann= 3 ,-1,0
       0      .1       0    87.8    .045       0   104.2      .1       0
#XS Ineff= 2 , 0
                           171.5         2316.01
Permanent Ineff=
       F       F
Bank Sta=87.8,104.2
XS Rating Curve= 0 ,0
Exp/Cntr(USF)=0,0
Exp/Cntr=0.3,0.1