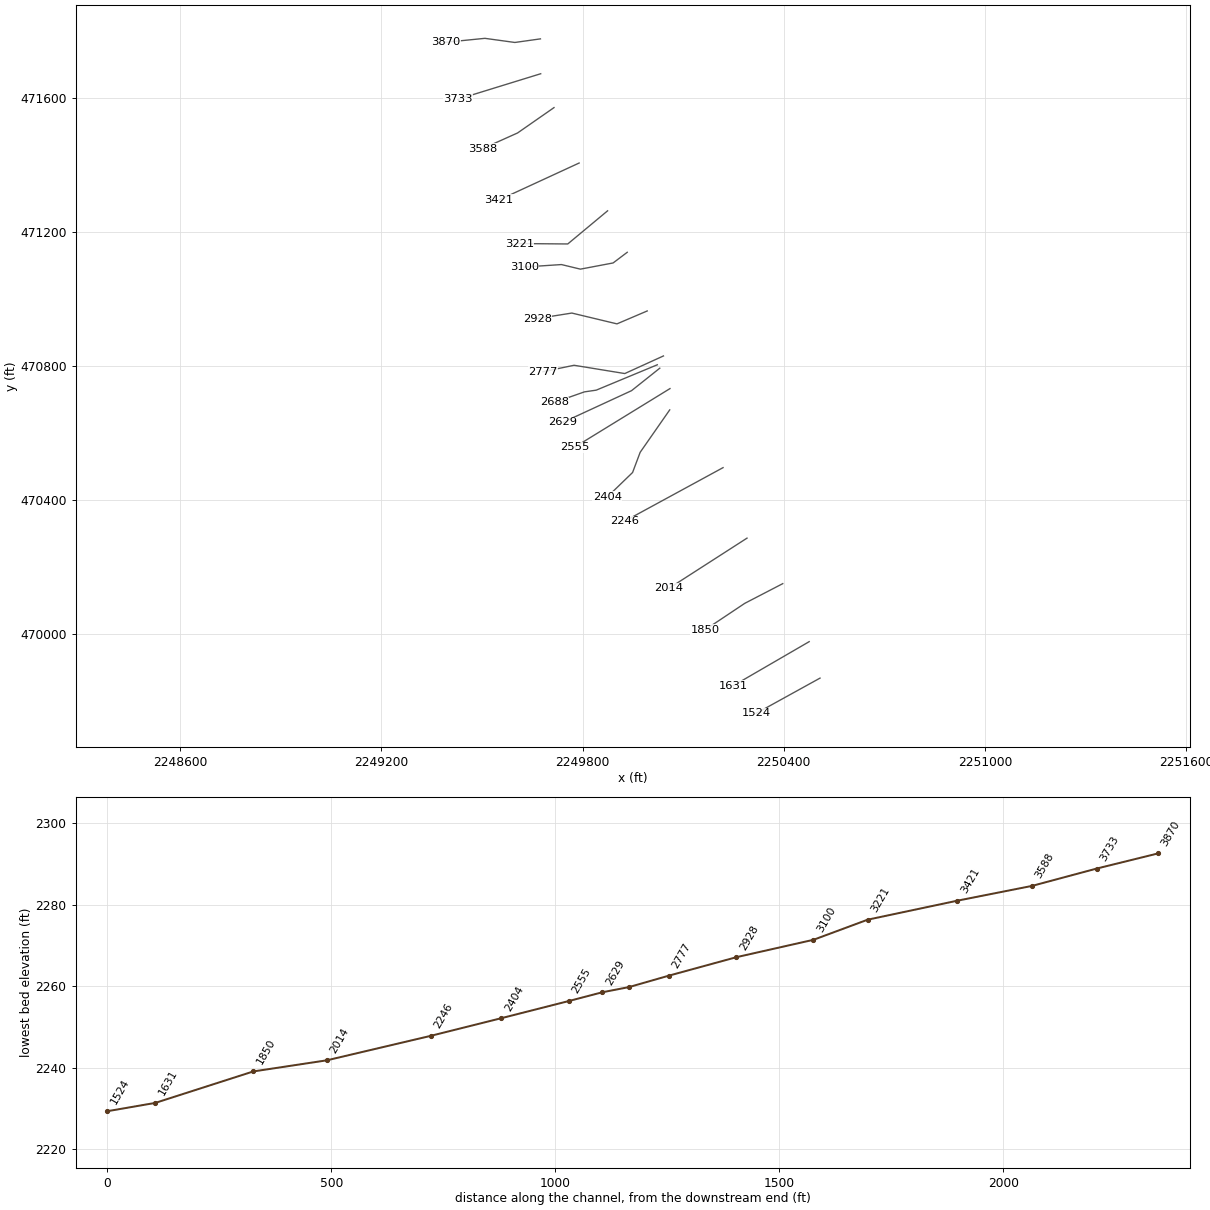
HEC-RAS study LAURELRN3.prj: LAURELRN3

--- LAURELRN3.g01 (geometry) --- (continued)

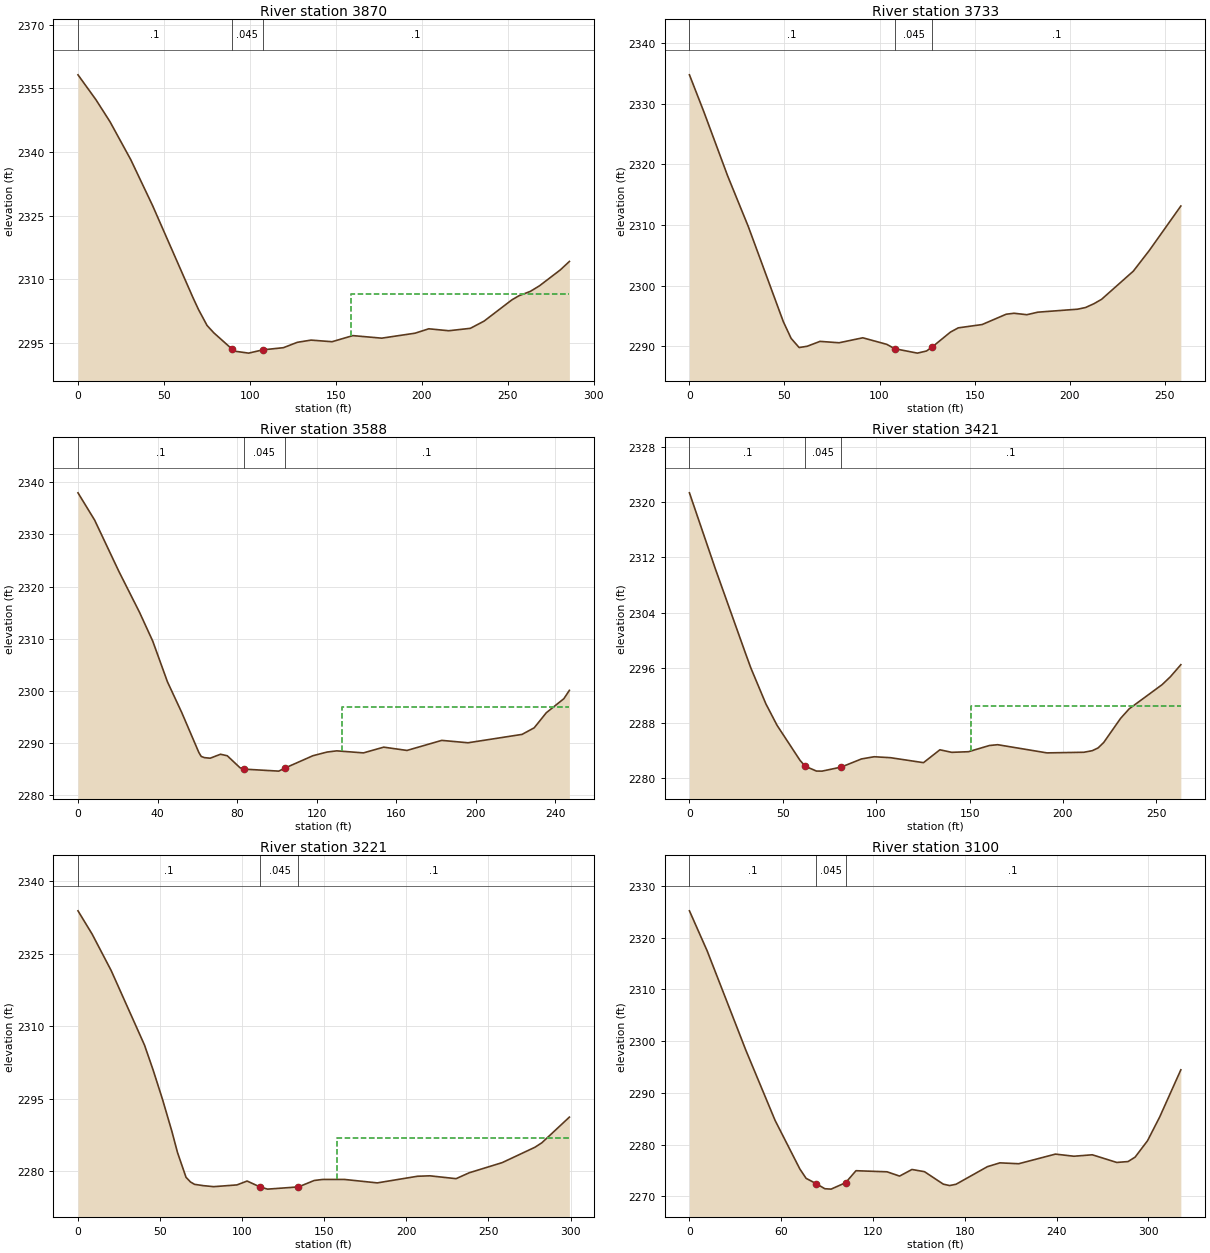
Type RM Length L Ch R = 1 ,3870    ,126.8,137,140.1
XS GIS Cut Line= 4
2249674.54610326471775.8723342492249598.33645478471765.146453869
2249508.91546618471777.4619193652249390.87861457471765.651618417
#Sta/Elev= 30
       0 2358.19    10.5 2352.29    18.6 2347.15    30.7 2338.19    43.4 2327.35
      67 2305.55    70.1 2302.85    75.1 2299.07    79.1 2297.31    89.6 2293.51
    91.3    2293    99.3 2292.55   107.5 2293.32   119.5 2293.83   127.6  2295.1
   135.6 2295.62   147.8 2295.24   159.9 2296.68   176.7 2296.08   196.1 2297.25
   204.1 2298.29   215.7 2297.83   228.3  2298.4   236.3 2300.11   252.4  2305.1
   256.4 2306.05   263.2 2307.12   268.5 2308.43   280.5 2312.14   285.9 2314.17
#Mann= 3 ,-1,0
       0      .1       0    89.6    .045       0   107.5      .1       0
#XS Ineff= 2 , 0
                          158.94         2306.52
Permanent Ineff=
       F       F
Bank Sta=89.6,107.5
XS Rating Curve= 0 ,0
Exp/Cntr(USF)=0,0
Exp/Cntr=0.3,0.1

Type RM Length L Ch R = 1 ,3733    ,137.5,144.4,146.8
XS GIS Cut Line= 2
2249675.33795665 471671.882380682249428.33780779471595.711676092
#Sta/Elev= 30
       0 2334.77     7.5 2328.74    20.1 2318.09      31  2309.7    49.4 2294.02
    53.5 2291.27    57.7 2289.76    61.9 2289.97    68.7 2290.78    78.7 2290.55
    91.2 2291.37   103.8 2290.29     108 2289.57   119.9 2288.84   124.7 2289.19
   127.8 2289.88   137.3 2292.31   141.4 2293.01     154 2293.56   166.6 2295.26
   170.7 2295.42   177.5 2295.18   183.3  2295.6   204.2 2296.09   208.4 2296.37
   212.8    2297   216.8 2297.72   233.5 2302.37   241.9 2305.78   258.5 2313.12
#Mann= 3 ,-1,0
       0      .1       0     108    .045       0   127.8      .1       0
Bank Sta=108,127.8
XS Rating Curve= 0 ,0
Exp/Cntr(USF)=0,0
Exp/Cntr=0.3,0.1

Type RM Length L Ch R = 1 ,3588    ,169.7,167,164.7
XS GIS Cut Line= 3
2249715.04363393 471570.89758315 2249606.3682801471495.277123016
2249501.60275876471448.262598527
#Sta/Elev= 30
       0 2337.99     8.4 2332.74    20.5 2322.97      31 2315.03    37.6 2309.54
      45 2301.73    52.2 2295.83    60.8 2288.17      62 2287.41    63.6 2287.18
    66.5 2287.07    71.7 2287.83    75.1 2287.54    81.5 2285.2483.388692284.977
     101 2284.59   103.9 2285.14   118.2 2287.55   125.3 2288.25   130.2 2288.48
   143.6 2288.09   153.8 2289.19   165.5 2288.56     183 2290.49   196.2 2290.03
   223.4 2291.64   229.5  2292.9   235.6  2295.8   244.4 2298.48   247.2 2300.09
#Mann= 3 ,-1,0
       0      .1       083.38869    .045       0   103.9      .1       0
#XS Ineff= 2 , 0
                          132.85         2296.99
Permanent Ineff=
       F       F
Bank Sta=83.38869,103.9
XS Rating Curve= 0 ,0
Exp/Cntr(USF)=0,0
Exp/Cntr=0.3,0.1

Type RM Length L Ch R = 1 ,3421    ,196.2,199.9,205.4
XS GIS Cut Line= 2
2249789.96377423471405.6546753252249551.09836082471295.465986164
#Sta/Elev= 30
       0 2321.39    13.8 2310.41    29.8 2298.24    32.8    2296    40.9 2290.75
    46.9 2287.62    59.2 2282.53      62 2281.67      68 2280.97      71 2280.96
    81.3 2281.55    92.1 2282.73    98.9 2283.05   107.7 2282.91   125.3 2282.19
   134.1 2284.06   140.4 2283.69   149.4 2283.78   160.6 2284.68     165  2284.8
   191.4 2283.61   211.2  2283.7   215.7 2283.93   218.8 2284.33   221.8 2285.12
   230.8 2288.61   235.4    2290   253.1 2293.53   257.5 2294.67   263.1 2296.42
#Mann= 3 ,-1,0
       0      .1       0      62    .045       0    81.3      .1       0
#XS Ineff= 2 , 0
                          150.72         2290.49
Permanent Ineff=
       F       F
Bank Sta=62,81.3
XS Rating Curve= 0 ,0
Exp/Cntr(USF)=0,0
Exp/Cntr=0.3,0.1

Type RM Length L Ch R = 1 ,3221    ,125.7,121.1,110.4
XS GIS Cut Line= 3
2249874.79485941471263.0624548362249756.02646694471164.261764914
2249611.20166298471165.431727335
#Sta/Elev= 30
       0 2333.82     8.6 2329.02    20.2 2321.49    40.5 2306.09    45.8 2300.89
    51.5 2294.84    57.2 2288.24    60.6 2283.89    65.8 2278.76    68.5 2277.79
      71  2277.3    76.3 2277.03    82.7 2276.82    96.8 2277.18     103 2277.98
   111.1 2276.73   115.5 2276.31   134.3 2276.77   143.9  2278.1   149.1 2278.31
   162.3 2278.31   182.3  2277.6   206.8 2278.97   214.3 2279.06   230.3 2278.47
   238.3 2279.69   258.4 2281.79   278.3 2284.96   282.5 2285.88   299.3 2291.19
#Mann= 3 ,-1,0
       0      .1       0   111.1    .045       0   134.3      .1       0
#XS Ineff= 2 , 0
                          157.49         2286.89
Permanent Ineff=
       F       F
Bank Sta=111.1,134.3
XS Rating Curve= 0 ,0
Exp/Cntr(USF)=0,0
Exp/Cntr=0.3,0.1

Type RM Length L Ch R = 1 ,3100    ,175.6,171.9,164.5
XS GIS Cut Line= 5
2249933.43092656 471139.426969972249891.27820655471107.627549608
2249793.76340657471089.1660424882249737.16313352471102.828177363
2249626.36485593471095.511727766
#Sta/Elev= 30
       0 2325.19    11.6 2317.44    36.9 2298.23      56 2284.67    72.2 2275.27
    76.3 2273.46   82.872272.442    88.5 2271.46    92.6 2271.38   102.1 2272.62
   108.9 2274.94   129.2 2274.73   137.4  2273.9   145.5 2275.18   153.7 2274.75
     166 2272.34   170.1 2272.07   174.3 2272.32   194.8 2275.72     203 2276.46
   215.3 2276.29   239.3 2278.15   251.4 2277.74   263.4 2278.02   279.4 2276.54
   286.8 2276.71   291.4 2277.57   299.5 2280.73   307.5 2285.35   321.3 2294.45
#Mann= 3 ,-1,0
       0      .1       0   82.87    .045       0   102.1      .1       0
Bank Sta=82.87,102.1
XS Rating Curve= 0 ,0
Exp/Cntr(USF)=0,0
Exp/Cntr=0.3,0.1

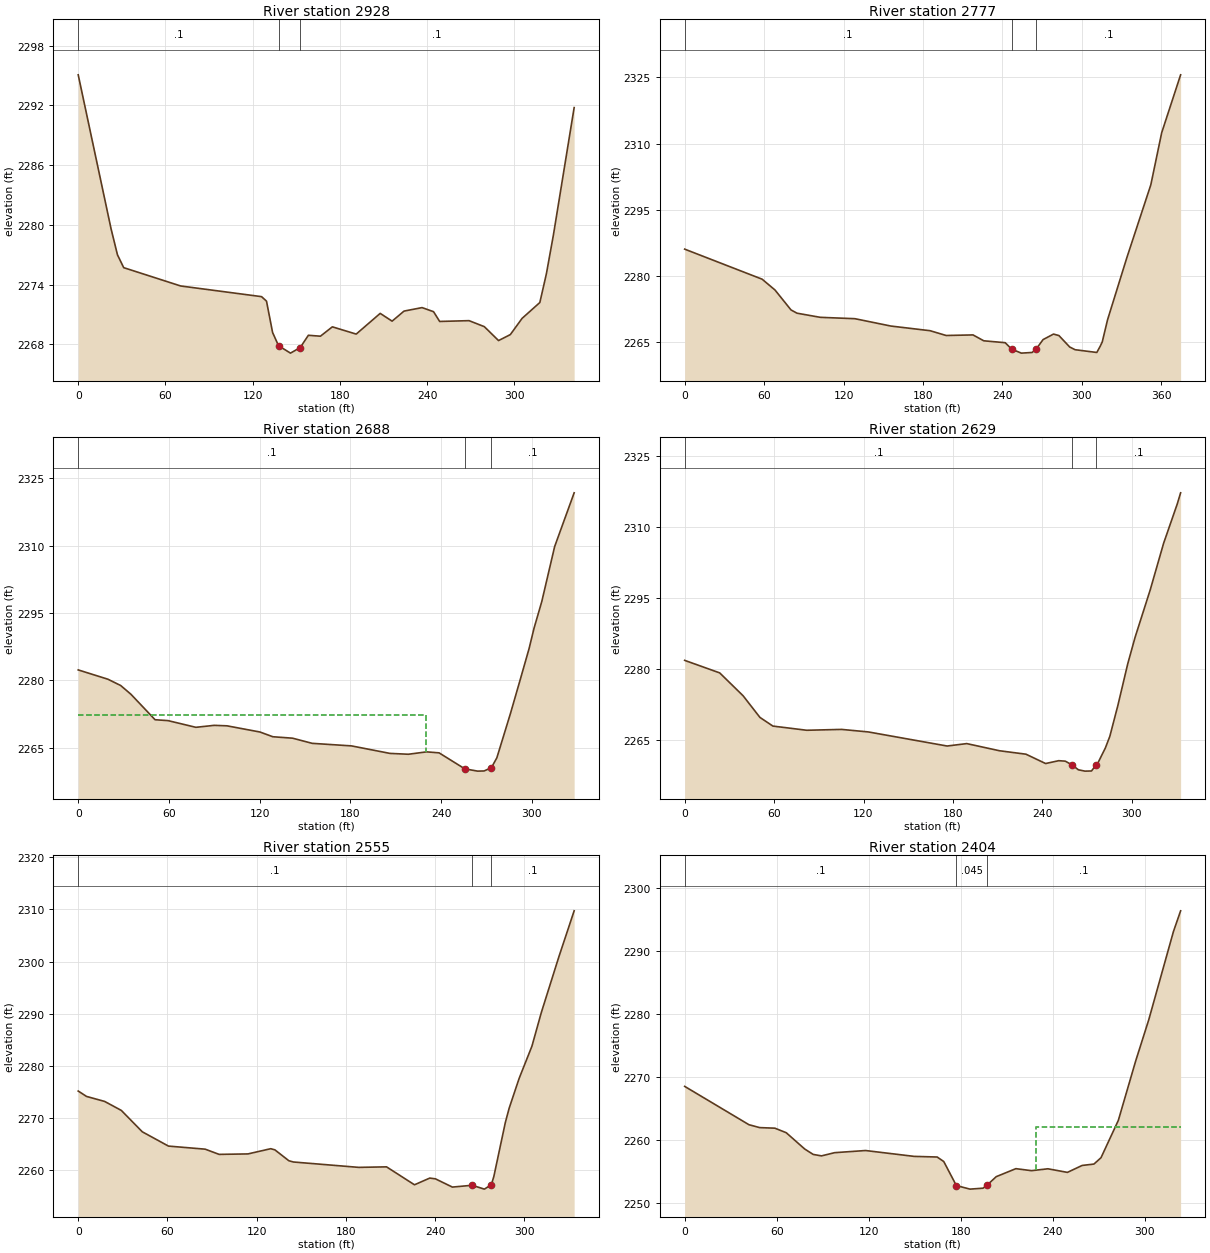
Type RM Length L Ch R = 1 ,2928    ,149.4,151.6,152.1
XS GIS Cut Line= 4
2249992.97896431470964.4732024842249902.75430991470925.966353268
2249768.18816429470958.2064702752249664.88517814470941.769184731
#Sta/Elev= 30
       0 2295.06    22.6  2279.6      27 2276.99    31.3  2275.7    70.5 2273.86
   126.1 2272.79   129.5 2272.34   133.7 2269.19   137.8 2267.86     146 2267.12
   152.7 2267.68   158.3 2268.91   166.6 2268.82   174.8 2269.76   191.2 2269.03
   207.7 2271.11   215.9 2270.33   224.1 2271.34   236.5 2271.69   244.4 2271.28
   248.6  2270.3   268.8 2270.38   279.3 2269.78   289.1 2268.38   297.2 2268.98
   305.3 2270.61   317.5  2272.2     322 2275.08   326.8 2278.95   341.1 2291.77
#Mann= 3 ,-1,0
       0      .1       0   137.8    .045       0   152.7      .1       0
Bank Sta=137.8,152.7
XS Rating Curve= 0 ,0
Exp/Cntr(USF)=0,0
Exp/Cntr=0.3,0.1

Type RM Length L Ch R = 1 ,2777    ,83.4,88.7,96.9
XS GIS Cut Line= 4
2250041.40105151470830.3070231972249926.03571253 470777.80100353
2249774.79872012470802.4911553712249682.14410533470783.193307016
#Sta/Elev= 30
       0  2286.1    58.5  2279.3    68.2 2276.86    80.3 2272.35    84.8 2271.61
   102.4 2270.67   128.6 2270.36   155.7  2268.7   185.4 2267.64   197.5 2266.56
   217.8 2266.69   225.9 2265.36   242.1 2264.93     247 2263.47   254.3 2262.57
   262.4 2262.72   265.4 2263.45   270.7 2265.63   278.6 2266.88   282.7 2266.54
   290.8 2263.96   294.9 2263.34   311.3 2262.72   313.8 2264.09   315.4 2265.09
   319.4  2270.1     334 2284.18   352.1 2300.66   360.3 2312.44   374.6 2325.54
#Mann= 3 ,-1,0
       0      .1       0     247    .045       0   265.4      .1       0
Bank Sta=247,265.4
XS Rating Curve= 0 ,0
Exp/Cntr(USF)=0,0
Exp/Cntr=0.3,0.1

Type RM Length L Ch R = 1 ,2688    ,57.6,58.8,60.2
XS GIS Cut Line= 4
2250023.06181652470803.9601677752249840.90427833 470728.30602893
2249805.64798062470723.1644855142249716.03822392470691.580718811
#Sta/Elev= 30
       0 2282.33    19.6 2280.26    28.1 2278.85    34.9 2276.89    50.8 2271.23
    59.4 2271.03    77.8 2269.54      90 2269.98    98.4 2269.87   120.1  2268.5
   128.7 2267.44   141.7 2267.12   154.7 2265.97   180.7  2265.4   206.1 2263.73
   218.3 2263.54   230.3 2264.07   238.6 2263.85   255.6 2260.29   264.1 2259.78
   268.4 2259.82   273.2 2260.56   276.8 2262.75   285.8 2272.64     292 2279.87
   298.1 2287.08   301.4 2291.64   306.5 2297.56     315  2309.8   327.9 2321.78
#Mann= 3 ,-1,0
       0      .1       0   255.6    .045       0   273.2      .1       0
#XS Ineff= 2 , 0
          229.95 2272.38
Permanent Ineff=
       F       F
Bank Sta=255.6,273.2
XS Rating Curve= 0 ,0
Exp/Cntr(USF)=0,0
Exp/Cntr=0.3,0.1

Type RM Length L Ch R = 1 ,2629    ,73.9,74.6,76.2
XS GIS Cut Line= 3
2250030.52689751470793.8451577472249946.34731788 470726.84508416
2249741.91119591470632.357800896
#Sta/Elev= 30
       0 2281.87    23.5 2279.23    39.2 2274.41    50.5 2269.85    59.2 2268.02
    81.9 2267.14   105.3 2267.32   123.2 2266.79   176.1 2263.82   189.3 2264.33
   211.3 2262.82     229  2262.1   242.2 2260.13     251 2260.73   255.4 2260.63
   259.8 2259.87   264.2 2258.81   268.6 2258.53     273 2258.56   276.2  2259.9
   277.4 2260.31   282.3 2263.41   285.3 2265.86   290.7 2272.38   297.3 2281.12
   302.2 2286.68   312.4 2296.72   321.4 2306.55   330.5 2314.78   332.8 2317.17
#Mann= 3 ,-1,0
       0      .1       0   259.8    .045       0   276.2      .1       0
Bank Sta=259.8,276.2
XS Rating Curve= 0 ,0
Exp/Cntr(USF)=0,0
Exp/Cntr=0.3,0.1

Type RM Length L Ch R = 1 ,2555    ,144.8,150.8,161
XS GIS Cut Line= 2
2250060.90807044470732.9839673132249776.64367999470558.297290629
#Sta/Elev= 30
       0 2275.19     5.6 2274.16    17.8  2273.2      29 2271.48    43.1 2267.38
    60.7 2264.64    85.4 2264.05    94.8 2263.05   114.2 2263.14   129.5 2264.14
   132.3 2263.92   141.7 2261.83   144.8 2261.59   188.7 2260.56   207.4 2260.66
   226.2 2257.22   236.5 2258.51   240.3 2258.36   251.7 2256.78     265 2257.13
   273.2 2256.39   277.9 2257.22   279.6 2258.84   287.3 2269.15   289.9 2271.92
   296.6 2277.62   305.2 2283.79   311.5 2290.23   323.2 2300.82   333.6 2309.74
#Mann= 3 ,-1,0
       0      .1       0     265    .045       0   277.9      .1       0
Bank Sta=265,277.9
XS Rating Curve= 0 ,0
Exp/Cntr(USF)=0,0
Exp/Cntr=0.3,0.1

Type RM Length L Ch R = 1 ,2404    ,168.2,158,148.7
XS GIS Cut Line= 4
2250060.10304592470669.4517607812249971.96230163470542.953470371
2249949.33216554470482.7133522422249874.02814131 470409.92623594
#Sta/Elev= 30
       0  2268.5    41.9 2262.41    48.9 2261.95    58.8 2261.86    66.2 2261.14
    78.3 2258.54    83.8 2257.69    89.2 2257.46    97.8 2257.97   117.9 2258.31
   149.6 2257.38   164.6 2257.28   168.9 2256.56   177.1 2252.75     186 2252.18
   194.5 2252.33  197.052252.796   203.1 2254.16   215.9 2255.43   226.1 2255.11
   236.8 2255.41   249.5 2254.84   259.1 2255.94   266.8 2256.16   271.4 2257.17
   282.7  2263.1     294 2272.53   302.5 2279.05   318.6 2293.07   323.3 2296.38
#Mann= 3 ,-1,0
       0      .1       0   177.1    .045       0  197.05      .1       0
#XS Ineff= 2 , 0
                          228.82         2261.98
Permanent Ineff=
       F       F
Bank Sta=177.1,197.05
XS Rating Curve= 0 ,0
Exp/Cntr(USF)=0,0
Exp/Cntr=0.3,0.1

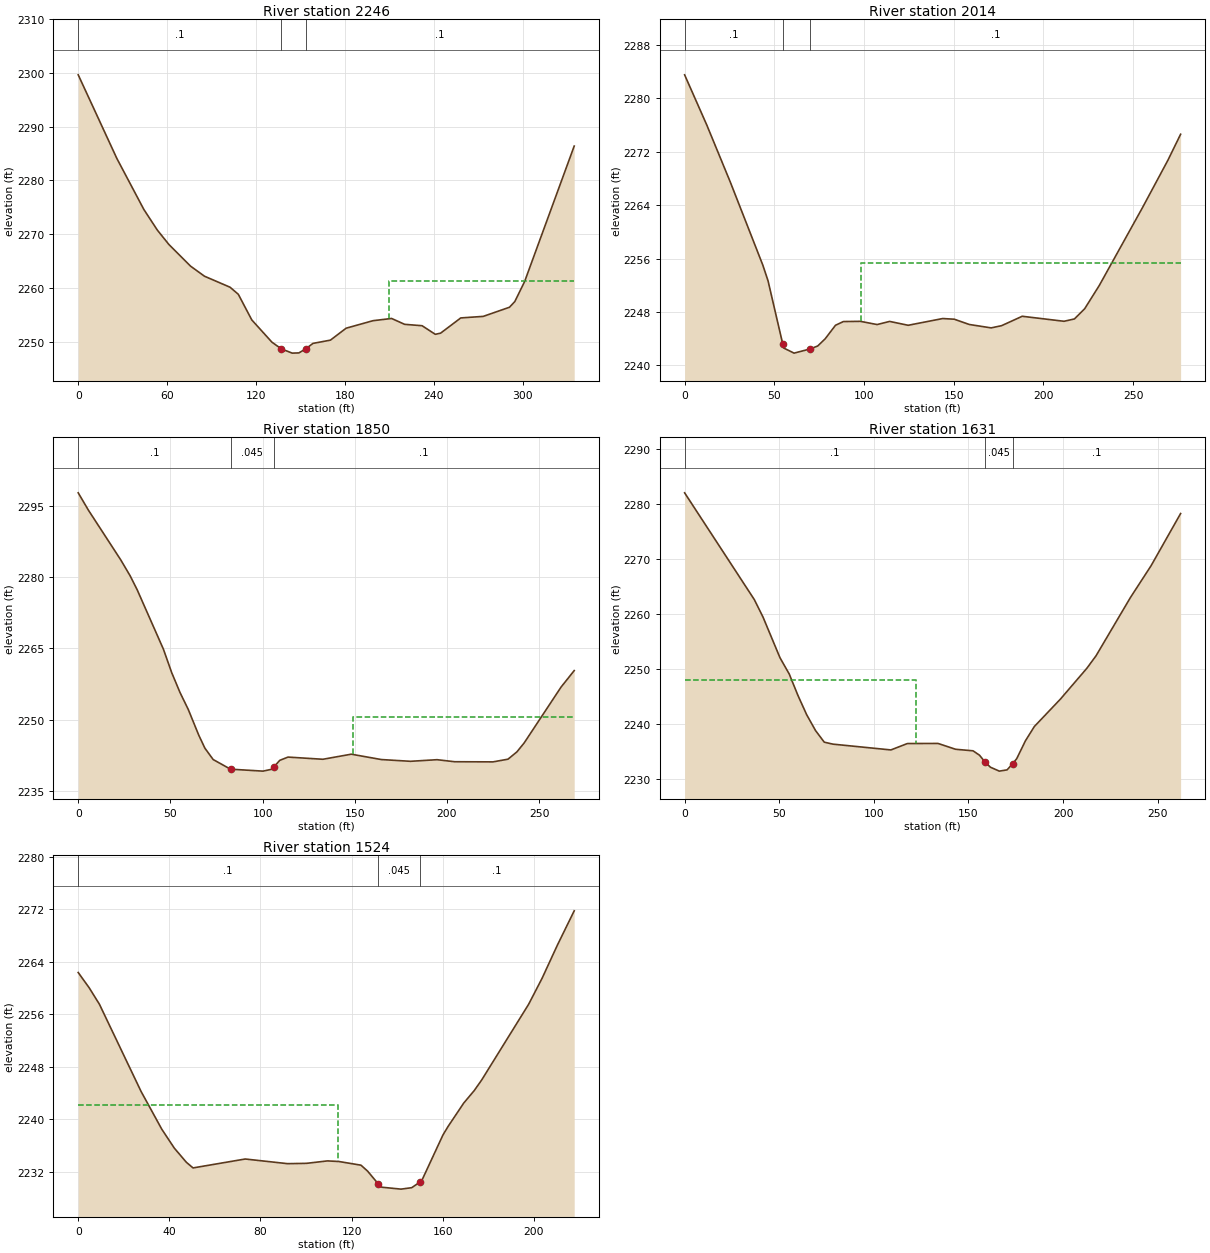
Type RM Length L Ch R = 1 ,2246    ,230.4,231.7,232.7
XS GIS Cut Line= 2
 2250219.0994969470497.2107568982249924.91402763470337.155827262
#Sta/Elev= 30
       0 2299.64    26.1 2284.07    44.3 2274.59    53.4 2270.75    61.2 2268.07
    75.9 2264.02    85.3 2262.15   102.5 2260.11   108.1 2258.79   117.2 2254.02
   130.8 2249.88   137.1 2248.64   144.5 2247.84     149 2247.88   153.6 2248.63
   158.5 2249.65   170.3 2250.26   180.9 2252.48   199.1 2253.88   211.6 2254.29
   220.4  2253.2   232.2 2252.94   241.1 2251.34   244.7 2251.56   258.3 2254.39
   273.5 2254.68   291.2 2256.38   294.8 2257.44   301.4 2261.15   334.9 2286.38
#Mann= 3 ,-1,0
       0      .1       0   137.1    .045       0   153.6      .1       0
#XS Ineff= 2 , 0
                          209.66         2261.19
Permanent Ineff=
       F       F
Bank Sta=137.1,153.6
XS Rating Curve= 0 ,0
Exp/Cntr(USF)=0,0
Exp/Cntr=0.3,0.1

Type RM Length L Ch R = 1 ,2014    ,165.8,164.3,163.5
XS GIS Cut Line= 2
2250290.59332881470287.0045312112250058.05493185 470137.45686956
#Sta/Elev= 30
       0 2283.53    12.4 2275.99    25.6 2267.38    43.6 2255.03    46.5 2252.69
   54.76 2243.15    55.2 2242.62      61 2241.85    69.9 2242.47    74.2 2242.92
    78.3 2243.98    84.1 2246.02    88.5 2246.58      98 2246.61   107.3 2246.13
   114.3  2246.6   124.6 2246.02   143.9 2247.03   150.3 2246.93   158.7 2246.14
   170.9 2245.63   176.7 2245.96   188.2 2247.37   211.5 2246.62   217.3 2246.97
     223 2248.49   231.2    2252   255.2 2263.62   269.4 2270.73   276.5 2274.63
#Mann= 3 ,-1,0
       0      .1       0   54.76    .045       0    69.9      .1       0
#XS Ineff= 2 , 0
                           98.07         2255.38
Permanent Ineff=
       F       F
Bank Sta=54.76,69.9
XS Rating Curve= 0 ,0
Exp/Cntr(USF)=0,0
Exp/Cntr=0.3,0.1

Type RM Length L Ch R = 1 ,1850    ,221.5,218.8,218.4
XS GIS Cut Line= 3
2250397.16838153470151.283277702 2250283.9424509470092.567507797
2250166.27455728470014.052964555
#Sta/Elev= 30
       0 2297.78     5.6 2294.08    23.1 2283.63    28.2 2280.26      32 2277.33
    46.2 2264.83    50.7 2259.88    55.2  2255.7    59.7 2252.11    65.4 2246.68
    68.7 2243.96    73.2 2241.56    82.62239.529   100.2 2239.12   104.8  2239.5
   106.1    2240   109.3 2241.39   113.8 2242.08   132.7 2241.62   148.1 2242.69
   164.4 2241.56   180.2 2241.19   194.6 2241.53   204.2  2241.1     225 2241.07
   233.1 2241.64   237.9 2243.17   241.8 2245.03   261.9 2256.85     269 2260.31
#Mann= 3 ,-1,0
       0      .1       0    82.6    .045       0   106.1      .1       0
#XS Ineff= 2 , 0
                          148.79         2250.44
Permanent Ineff=
       F       F
Bank Sta=82.6,106.1
XS Rating Curve= 0 ,0
Exp/Cntr(USF)=0,0
Exp/Cntr=0.3,0.1

Type RM Length L Ch R = 1 ,1631    ,107.5,107.3,107
XS GIS Cut Line= 2
2250475.99472266469978.2751395252250249.25265798469846.725078679
#Sta/Elev= 30
       0 2281.97    36.8 2262.59    41.4 2259.42    50.4 2252.01    55.3 2249.04
    59.9 2245.15    64.5 2241.66    69.2 2238.77    73.8 2236.67    78.4 2236.31
     109 2235.26   117.7 2236.42   133.9 2236.44   143.2 2235.38   152.4  2235.1
   155.8 2234.31   158.7 2233.09   161.6 2232.12   166.3 2231.41   170.4 2231.64
   173.3 2232.73   175.5 2233.68   180.1 2236.92   184.8 2239.51   198.6  2244.5
   212.5 2250.07   217.4 2252.36   235.6 2262.96   246.5 2268.73   262.1 2278.21
#Mann= 3 ,-1,0
       0      .1       0   158.7    .045       0   173.3      .1       0
#XS Ineff= 2 , 0
          122.22 2248.04
Permanent Ineff=
       F       F
Bank Sta=158.7,173.3
XS Rating Curve= 0 ,0
Exp/Cntr(USF)=0,0
Exp/Cntr=0.3,0.1

Type RM Length L Ch R = 1 ,1524    ,211.5,212.5,213.4
XS GIS Cut Line= 2
 2250508.3412977469869.5857833082250317.70911362469764.409405883
#Sta/Elev= 30
       0 2262.38     4.8 2260.06     9.3 2257.55    27.6 2244.25    36.7 2238.49
    42.2 2235.61    47.5 2233.45    50.4  2232.6    73.3 2233.96    91.9 2233.25
   100.2  2233.3   109.4 2233.67   114.4 2233.58   124.1 2233.02     127 2232.12
  131.582230.216   133.3 2229.66   141.7 2229.37   146.4 2229.59   149.9 2230.43
   150.9 2230.75   160.1 2237.63   162.3  2238.9   169.2 2242.48   173.8 2244.38
   177.1 2246.01   197.7 2257.54   203.6  2261.5   210.3 2266.54   217.7 2271.78
#Mann= 3 ,-1,0
       0      .1       0  131.58    .045       0   149.9      .1       0
#XS Ineff= 2 , 0
           114.2 2242.24
Permanent Ineff=
       F       F
Bank Sta=131.58,149.9
XS Rating Curve= 0 ,0
Exp/Cntr(USF)=0,0
Exp/Cntr=0.3,0.1