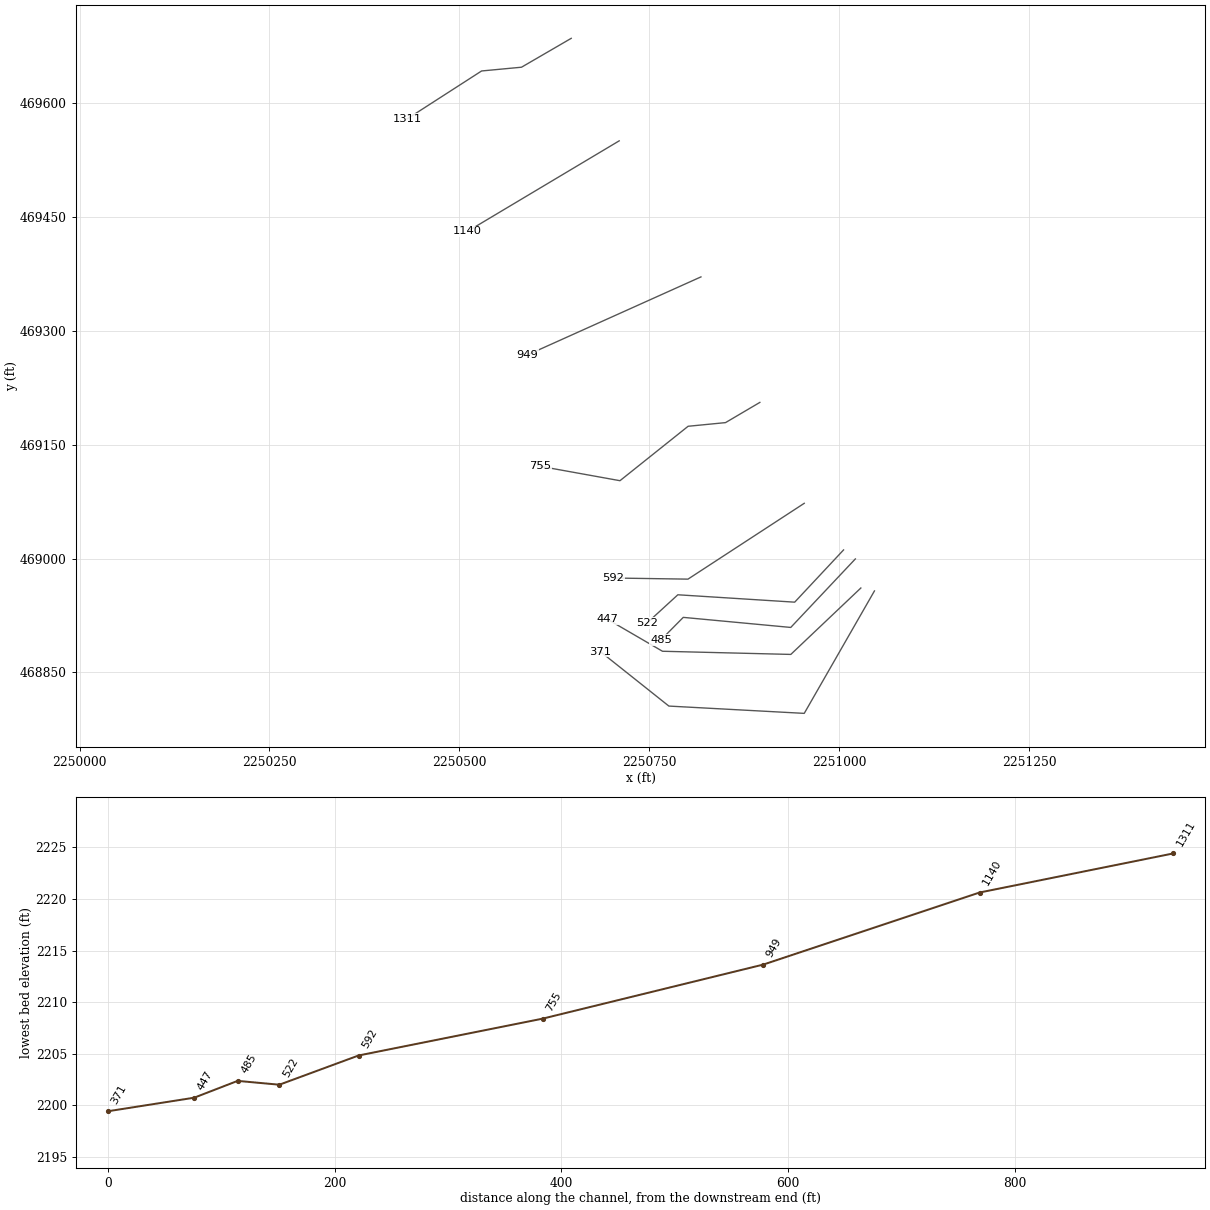
HEC-RAS study LAURELRN3.prj: LAURELRN3

--- LAURELRN3.g01 (geometry) --- (continued)

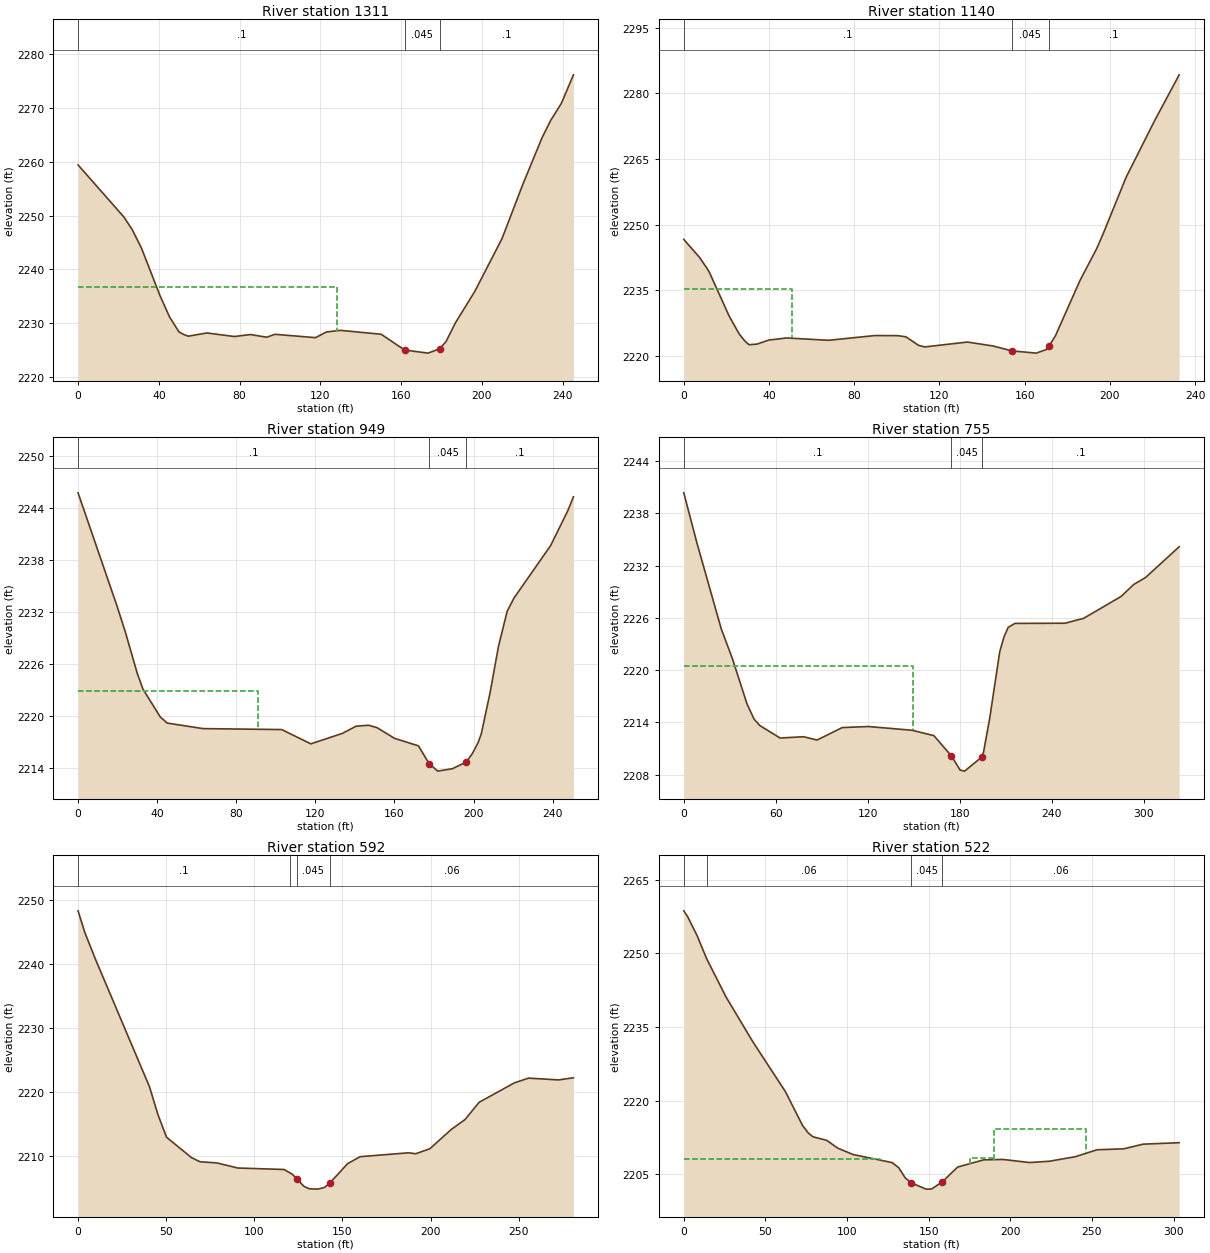
Type RM Length L Ch R = 1 ,1311    ,171.7,171.1,170.7
XS GIS Cut Line= 4
2250647.31808021469684.9156054022250581.85554588469646.893660198
2250529.30094913469641.9489192472250431.10239553469578.707364493
#Sta/Elev= 30
       0 2259.44    22.6 2249.79    26.8 2247.42    31.4 2243.96    40.6  2235.1
    45.3 2231.16    49.9 2228.41    51.9 2227.96    54.5 2227.57    63.8 2228.17
    77.4 2227.51    85.4 2227.88    93.4 2227.38    97.5 2227.92   117.6  2227.3
   122.9 2228.35   129.9 2228.66   150.1 2227.93   161.7    2225   173.3 2224.42
   179.1 2225.24   182.2 2226.57   186.9 2230.08   196.4 2235.87   209.9  2245.7
   220.2 2255.79   229.7 2264.45     234  2267.7   239.3 2270.88   245.3  2276.2
#Mann= 3 ,-1,0
       0      .1       0   161.7    .045       0   179.1      .1       0
#XS Ineff= 2 , 0
          128.42 2236.68
Permanent Ineff=
       F       F
Bank Sta=161.7,179.1
XS Rating Curve= 0 ,0
Exp/Cntr(USF)=0,0
Exp/Cntr=0.3,0.1

Type RM Length L Ch R = 1 ,1140    ,192.2,190.8,188.9
XS GIS Cut Line= 2
2250710.47714806469549.9481987912250510.80636904 469430.80308374
#Sta/Elev= 30
       0 2246.61     7.3 2242.56      11 2239.93      12 2239.11    21.3 2229.09
      26 2225.02    28.5 2223.48    30.6 2222.55    34.3 2222.69    39.9 2223.61
    48.3  2224.1    67.9 2223.56    89.8 2224.65   100.5 2224.62   104.3 2224.35
   110.2  2222.4   113.1 2222.05   133.1 2223.16   145.2 2222.26   153.9 2221.15
   165.4 2220.63   170.4  2221.5   171.4 2222.23   174.4 2224.57     186 2237.27
   193.7 2244.42   196.7 2247.76   207.6 2260.81     221 2273.77   232.5 2284.22
#Mann= 3 ,-1,0
       0      .1       0   153.9    .045       0   171.4      .1       0
#XS Ineff= 2 , 0
           50.66  2235.2
Permanent Ineff=
       F       F
Bank Sta=153.9,171.4
XS Rating Curve= 0 ,0
Exp/Cntr(USF)=0,0
Exp/Cntr=0.3,0.1

Type RM Length L Ch R = 1 ,949     ,191.4,194.8,198.8
XS GIS Cut Line= 2
2250818.11859683469370.8196809912250589.68865211469268.108374912
#Sta/Elev= 30
       0 2245.79    19.7 2232.72    23.9 2229.73    29.9 2224.97    32.8 2223.13
    41.6  2219.9    45.1  2219.2    63.2 2218.56     103 2218.45   117.7  2216.8
   133.7 2218.01   140.6 2218.84   146.9 2218.95   151.2 2218.67     160 2217.44
   172.1 2216.57   177.6 2214.49   181.9 2213.65   189.3 2213.93   196.3  2214.7
   199.5 2215.72   202.4    2217   203.9 2217.96   208.3 2222.66   212.6 2228.07
     217 2232.12   220.5 2233.66     239 2239.71   247.8  2243.8   250.5 2245.33
#Mann= 3 ,-1,0
       0      .1       0   177.6    .045       0   196.3      .1       0
#XS Ineff= 2 , 0
            91.2 2222.88
Permanent Ineff=
       F       F
Bank Sta=177.6,196.3
XS Rating Curve= 0 ,0
Exp/Cntr(USF)=0,0
Exp/Cntr=0.3,0.1

Type RM Length L Ch R = 1 ,755     ,163.3,162.4,160.7
XS GIS Cut Line= 5
2250895.67085903469205.568635786 2250850.4810235469178.957464851
2250801.21916151469174.138369657 2250711.4912598469102.487171381
2250606.94415153469121.349035868
#Sta/Elev= 30
       0 2240.36     8.7 2234.52    24.4 2224.76    31.9 2221.22    41.2 2216.14
    45.8 2214.39    49.6 2213.64    62.8 2212.21    78.1 2212.36    86.9 2211.98
   103.3 2213.41   120.4 2213.53   148.9  2213.1   163.1 2212.48   174.5 2210.16
   180.2 2208.53   183.1 2208.41   194.4 2210.04   195.4 2210.55   199.6 2214.62
     206 2222.11   208.7 2223.78   211.5 2224.91   215.9 2225.37   248.6 2225.39
   260.8 2225.96   285.2 2228.47   293.3 2229.83   301.1 2230.64     323 2234.17
#Mann= 3 ,-1,0
       0      .1       0   174.5    .045       0   194.4      .1       0
#XS Ineff= 2 , 0
          149.36 2220.52
Permanent Ineff=
       F       F
Bank Sta=174.5,194.4
XS Rating Curve= 0 ,0
Exp/Cntr(USF)=0,0
Exp/Cntr=0.3,0.1

Type RM Length L Ch R = 1 ,592     ,79.1,69.9,60.8
XS GIS Cut Line= 3
2250954.10836608469072.710386228 2250801.0274355 468972.87499672
 2250702.6710888468974.354039528
#Sta/Elev= 30
       0 2248.34     3.9 2244.91     9.7 2240.89    40.5 2220.87    45.3 2216.51
    50.2 2212.96    64.4 2209.76    69.2 2209.12    78.7 2208.94    90.7 2208.14
   116.9 2207.91   121.7 2207.15  124.372206.367   128.2 2205.27   131.2  2204.9
     136 2204.84   139.8  2205.1   142.7 2205.74   152.9 2208.81     160 2209.91
   187.6 2210.52   191.6 2210.37   199.6 2211.15   211.7 2214.15   219.6 2215.72
   227.6 2218.42   247.6 2221.45   255.6 2222.19   272.7 2221.91   281.1 2222.25
#Mann= 4 ,-1,0
       0      .1       0     120     .06       0  124.37    .045       0
   142.7     .06       0
Bank Sta=124.37,142.7
XS Rating Curve= 0 ,0
Exp/Cntr(USF)=0,0
Exp/Cntr=0.5,0.3

Type RM Length L Ch R = 1 ,522     ,37.3,36.8,37.2
XS GIS Cut Line= 4
2251005.87486434469011.3301097162250941.53650221468942.554619166
 2250787.6960046468952.2810976752250747.06985585468915.086931037
#Sta/Elev= 30
       0 2258.65     2.5 2257.38     8.3  2253.5      14 2248.91    25.9 2241.11
    42.3    2232    62.2 2221.88    72.8 2214.93    76.3 2213.42    79.1 2212.67
    87.6 2211.93    94.2 2210.37   103.6 2209.06   127.6 2207.41   131.6 2206.39
   135.6 2204.31   139.4 2203.28   148.4 2202.01   151.7 2202.03   158.2 2203.45
   167.7  2206.5   183.7 2207.97   195.5 2208.05   211.8 2207.42   223.8 2207.68
   239.8 2208.61   253.1 2210.02   269.4 2210.21   281.3 2211.16   303.4 2211.46
#Mann= 4 ,-1,0
       0      .1       0      14     .06       0   139.4    .045       0
   158.2     .06       0
#XS Ineff= 3 ,-1
       0     120  2208.2     175  190.19  2208.3  190.19  246.59 2214.26
Permanent Ineff=
       F       F       F
Bank Sta=139.4,158.2
XS Rating Curve= 0 ,0
Exp/Cntr(USF)=0,0
Exp/Cntr=0.5,0.3

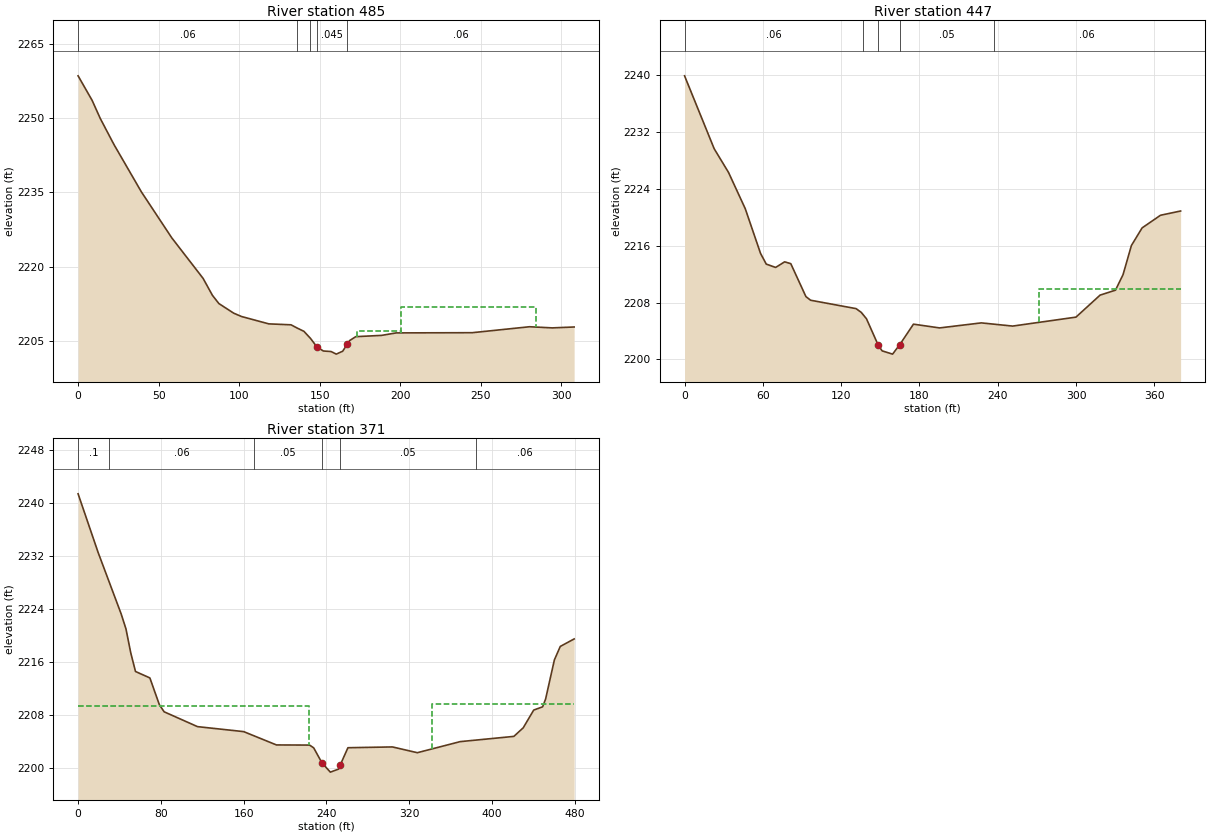
Type RM Length L Ch R = 1 ,485     ,37,38.4,39.6
XS GIS Cut Line= 4
2251021.40481382468999.4977672562250936.35985239468909.276155996
2250794.83540489468922.5335964782250765.36873522468892.773382049
#Sta/Elev= 30
       0 2258.49     8.7 2253.55    13.8 2249.87    22.3 2244.62    39.3 2235.09
    58.2 2225.81    77.6 2217.66    83.4 2214.24    87.4 2212.58    96.6 2210.64
   101.5 2209.96   118.4 2208.48   132.2 2208.29   136.2 2207.61   140.2 2206.98
   144.3 2205.55   148.3 2203.83   152.3 2203.01   157.1  2202.9   160.3 2202.38
   164.3 2202.97167.09872204.383   168.6 2205.11   172.4  2205.9   188.5 2206.16
   197.5 2206.66   244.7  2206.7   280.3  2207.9   294.4 2207.67     308 2207.85
#Mann= 5 ,-1,0
       0     .06       0   136.2     .05       0   144.3     .06       0
   148.3    .045       0167.0987     .06       0
#XS Ineff= 3 ,-1
       0  137.99 2206.73  173.05  200.67    2207  200.67  284.56 2211.91
Permanent Ineff=
       F       F       F
Bank Sta=148.3,167.0987
XS Rating Curve= 0 ,0
Exp/Cntr(USF)=0,0
Exp/Cntr=0.5,0.3

Type RM Length L Ch R = 1 ,447     ,76.5,76,75.8
XS GIS Cut Line= 4
2251028.65076429468961.2053480342250936.43351058468873.747694516
2250767.46770379468877.9123446842250694.88380087468920.153796383
#Sta/Elev= 30
       0 2239.95    22.7 2229.68    33.7 2226.34    46.5 2221.24    58.2 2214.95
    62.6 2213.43    69.8 2212.96    76.7 2213.75    81.4 2213.49      93 2208.85
    96.6 2208.34   131.4 2207.16   135.4 2206.63   139.4 2205.73   148.5 2201.97
   151.4 2201.21   159.4 2200.75   164.9 2202.09   175.4 2204.97   195.4 2204.44
   227.4 2205.15   251.4  2204.7   299.9 2205.96   318.4 2209.06   330.2 2209.76
     336 2211.95   342.4 2216.05   350.6 2218.53   364.7 2220.31   380.1 2220.91
#Mann= 5 ,-1,0
       0     .06       0  137.09     .05       0   148.5    .045       0
   164.9     .05       0  237.09     .06       0
#XS Ineff= 2 , 0
                          271.82         2209.93
Permanent Ineff=
       F       F
Bank Sta=148.5,164.9
XS Rating Curve= 0 ,0
Exp/Cntr(USF)=0,0
Exp/Cntr=0.3,0.1

Type RM Length L Ch R = 1 ,371     ,,,
XS GIS Cut Line= 4
2251046.54854155468957.3450472412250954.10836608 468796.12938122
2250775.88370777468805.7431594692250685.66209651468877.476735635
#Sta/Elev= 30
       0 2241.42    19.4 2232.56    41.7 2223.28    46.3 2221.03    50.9 2217.44
    55.5 2214.62    69.4 2213.65    78.6  2209.6    83.2 2208.54   115.5  2206.3
   160.1 2205.55   191.8 2203.54   223.8 2203.52   227.8  2203.1   235.8 2200.83
   243.9 2199.44   251.9  2199.9   253.3 2200.47   260.9 2203.12   303.9 2203.24
     328 2202.37   369.4 2204.04   421.3 2204.83   430.4 2206.13   440.5  2208.8
   449.1 2209.29     452 2210.46   460.5 2216.37   466.2  2218.4   479.6 2219.53
#Mann= 6 ,-1,0
       0      .1       0      30     .06       0     170     .05       0
   235.8    .045       0   253.3     .05       0  384.32     .06       0
#XS Ineff= 2 , 0
          223.61 2209.43  341.85         2209.71
Permanent Ineff=
       F       F
Bank Sta=235.8,253.3
XS Rating Curve= 0 ,0
Exp/Cntr(USF)=0,0
Exp/Cntr=0.3,0.1
LCMann Table=0

Chan Stop Cuts=-1
Use User Specified Reach Order=0
Composite Channel Slope=5